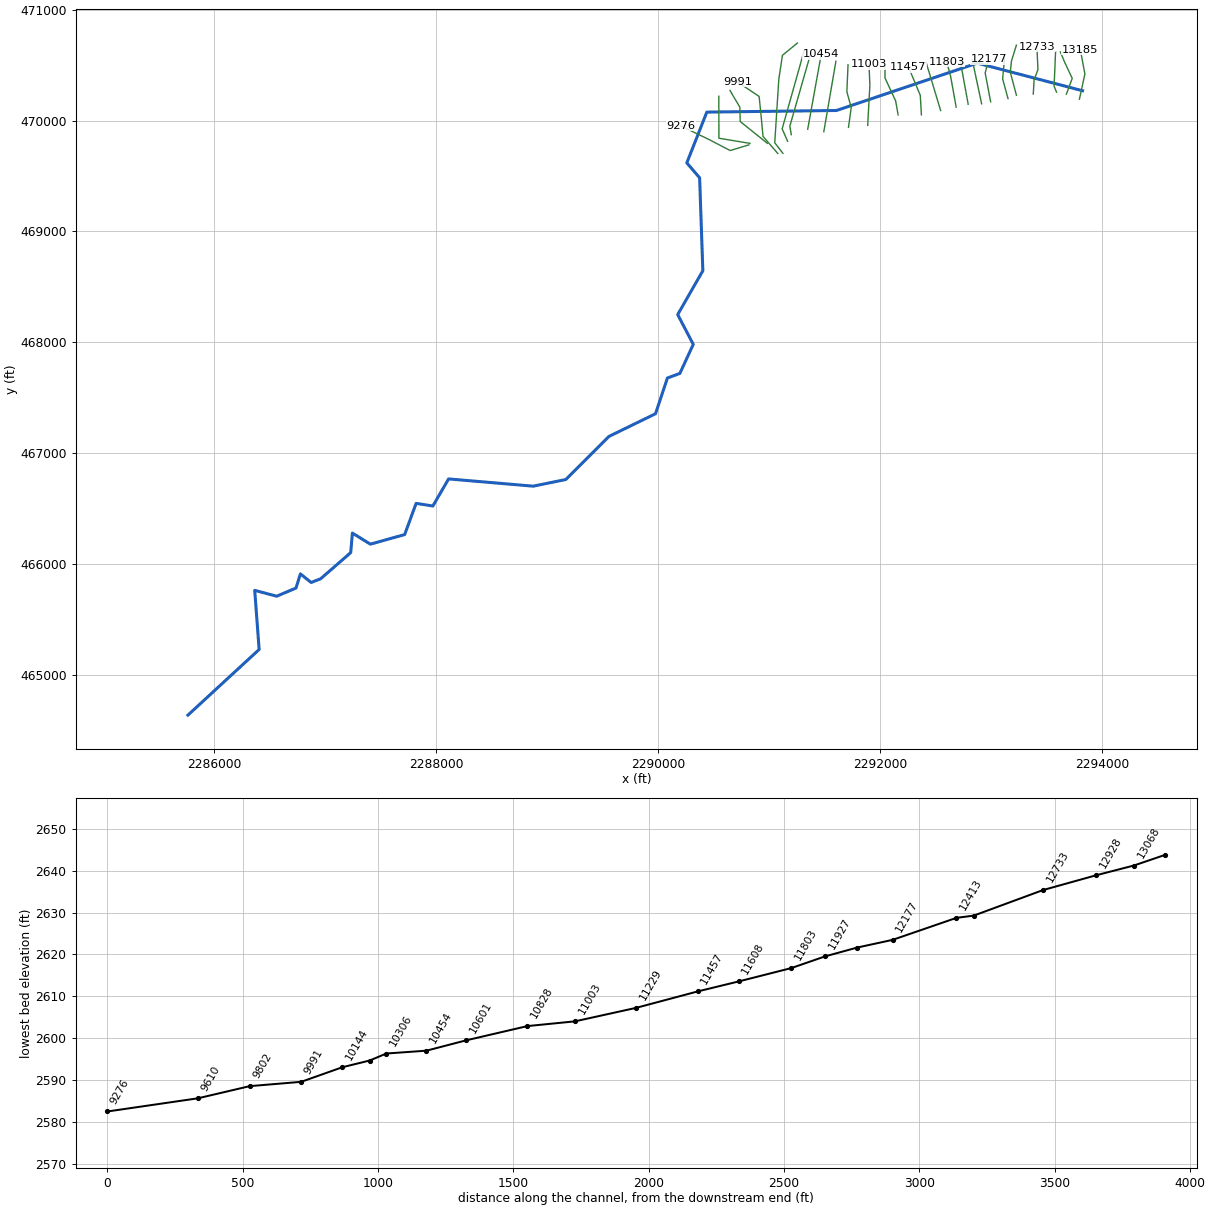
--- SGRCMPRN.prj (project) ---

Proj Title=SGRCMPRN
Current Plan=p01
Default Exp/Contr=0,0
English Units
Geom File=g01
Flow File=f01
Plan File=p01
Background Map Layer=Inundation Boundary (01pct Value_0)
Background Map Layer=Inundation Boundary (01pct Value_0)
BEGIN DESCRIPTION:
----------MODEL BY WOOD PLC 2021----------
Stream Name: Sugar Camp Run
Flood Zone: Approximate / Detailed alternating
Pocahontas County, WV
HEC-RAS Version: RAS 6.1
Vertical Datum: NAVD88
Projection: NAD 1983 StatePlane West Virginia S FIPS 4702 (US Feet)
Terrain: 1-meter LIDAR (FEMA Region III 3DEP collected 2016-2018)
Land Use: 2019 NLCD
Hydrologic Method:
WV SIR2010-5033 regression equations
Model Notes:
Zone A from 6581 to 13207
Zone AE from XS 0 to 6486
Channel burning for XS 6489 and 6408
Coincident peak with Knapp Creek, XS 124820
END DESCRIPTION:
DSS File=dss
DSS Export Rating Curves= 0
DSS Export Rating Curve Sorted= 0
DSS Export Volume Flow Curves= 0
DXF OffsetX= 0
DXF OffsetY= 0
DXF ScaleX= 0
DXF ScaleY= 0

--- SGRCMPRN.p01 (plan) ---

Plan Title=Floodplain
Program Version=6.10
Short Identifier=Floodplain
Geom File=g01
Flow File=f01
Subcritical Flow
K Sum by GR= 0
Std Step Tol= 0.01
Critical Tol= 0.01
Num of Std Step Trials= 20
Max Error Tol= 0.3
Flow Tol Ratio= 0.001
Split Flow NTrial= 30
Split Flow Tol= 0.02
Split Flow Ratio= 0.02
Log Output Level= 0
Friction Slope Method= 1
Unsteady Friction Slope Method= 2
Unsteady Bridges Friction Slope Method= 1
Parabolic Critical Depth
Global Vel Dist= 0 , 0 , 0
Global Log Level= 0
CheckData=True
Encroach Param=-1 ,5,5, 2
Encroach River=SGRCMPRN
Encroach Reach=Main
Encroach Node=6757
       1     151     263
Encroach Node=6581
       1  228.31     365
Encroach Node=6486
       1     287     333
Encroach Node=6405
       1     263  290.08
Encroach Node=6288
       1     197     253
Encroach Node=6112
       1     285   318.1
Encroach Node=5976
       1   339.3  374.86
Encroach Node=5941
       1     296     346
Encroach Node=5904
       1  288.03  360.71
Encroach Node=5789
       1     257   306.4
Encroach Node=5651
       1  287.18  344.35
Encroach Node=5407
       1     246     302
Encroach Node=5201
       1  268.79     339
Encroach Node=5075
       1     211  280.15
Encroach Node=4852
       1  237.35     326
Encroach Node=4563
       1  222.19   343.5
Encroach Node=4312
       1  244.09  358.32
Encroach Node=4005
       1  199.24  308.58
Encroach Node=3729
       1  210.98     346
Encroach Node=3414
       1   143.8  216.73
Encroach Node=3246
       1   125.7  207.66
Encroach Node=2833
       1     311     437
Encroach Node=2581
       1   307.2  365.33
Encroach Node=2365
       1   252.4  351.68
Encroach Node=2063
       1  219.42  338.39
Encroach Node=1831
       1     200     360
Encroach Node=1449
       1  457.59   552.1
Encroach Node=1177
       1  267.15  328.61
Encroach Node=1038
       1   163.6  239.73
Encroach Node=941
       1   134.3     241
Encroach Node=740
       1   132.9   198.1
Encroach Node=657
       1   161.2  228.11
Encroach Node=594
       1     255  324.68
Encroach Node=449
       1   214.1     274
Encroach Node=299
       1     238     323
Encroach Node=0
       1  832.01   923.9
Computation Interval=0.1SEC
Output Interval=1SEC
Instantaneous Interval=Max Profile
Mapping Interval=1HOUR
Computation Time Step Use Courant=        0
Computation Time Step Use Time Series=    0
Computation Time Step Count To Double=0
Computation Time Step Max Doubling=0
Computation Time Step Max Halving=0
Computation Time Step Residence Courant=0
Run HTab= 0
Run UNet= 0
Run Sediment= 0
Run PostProcess= 0
Run WQNet= 0
Run RASMapper=-1
UNET Theta= 0
UNET Theta Warmup= 0
UNET ZTol= 0
UNET ZSATol= 0
UNET MxIter= 0
UNET Max Iter WO Improvement= 0
UNET MaxInSteps= 0
UNET DtIC= 0
UNET DtMin= 0
UNET MaxCRTS= 0
UNET WFStab= 0
UNET SFStab= 0
UNET WFX= 1
UNET SFX= 1
UNET Gravity=32.174
UNET 1D Methodology=Finite Difference
UNET DSS MLevel= 1
UNET Pardiso=0
UNET DZMax Abort= 0
UNET Use Existing IB Tables= 0
UNET Froude Reduction=False
UNET Froude Limit= 0
UNET Froude Power= 0
UNET D1 Cores= 0
UNET WindReference=Eulerian
UNET WindDragFormulation=Hsu (1988)
UNET D2 Coriolis=0
UNET D2 Cores= 0
UNET D2 Theta= 1
UNET D2 Theta Warmup= 1
UNET D2 Z Tol= 0.01
UNET D2 Volume Tol= 0.01
UNET D2 Max Iterations= 20
UNET D2 Equation= 0
UNET D2 RampUpFraction=0.1
UNET D2 TimeSlices= 1
UNET D2 Turbulence Formulation=Non-Conservative (original)
UNET D2 Eddy Viscosity=0.3
UNET D2 Transverse Eddy Viscosity=0.1
UNET D2 Smagorinsky Mixing=0
UNET D2 BCVolumeCheck=0
UNET D2 Cores=0
UNET D2 SolverType=PARDISO (Direct)
UNET D2 Minimum Iterations= 2147483647
UNET D2 Maximum Iterations= 2147483647
UNET D2 Restart Number= 10
UNET D2 Relaxation Coeff=1.3
UNET D2 SOR Precondition Iterations= 10
UNET D2 ILUT Maximum Fill= 8
UNET D2 ILUT Tolerance=1E-08
UNET D1D2 MaxIter= 0
UNET D1D2 ZTol=0.01
UNET D1D2 QTol=0.1
UNET D1D2 MinQTol=1
DSS File=dss
Write IC File= 0
Write IC File at Fixed DateTime=0
Write IC File at Sim End=0
Echo Input=False
Echo Parameters=False
Echo Output=False
Write Detailed= 0
HDF Write Warmup=0
HDF Write Time Slices=0
HDF Flush=0
HDF Compression= 1
HDF Chunk Size= 1
HDF Spatial Parts= 1
HDF Use Max Rows=0
HDF Fixed Rows= 1
Calibration Method= 0
Calibration Iterations= 20
Calibration Max Change=0.05
Calibration Tolerance=0.2
Calibration Maximum=1.5
Calibration Minimum=0.5
Calibration Optimization Method= 1
WQ AD Non Conservative
WQ ULTIMATE=-1
WQ Max Comp Step=1HOUR
WQ Output Interval=15MIN
WQ Output Selected Increments= 0
WQ Output face flow=0
WQ Output face velocity=0
WQ Output face area=0
WQ Output face dispersion=0
WQ Output cell volume=0
WQ Output cell surface area=0
WQ Output cell continuity=0
WQ Output cumulative cell continuity=0
WQ Output face conc=0
WQ Output face dconc_dx=0
WQ Output face courant=0
WQ Output face peclet=0
WQ Output face adv mass=0
WQ Output face disp mass=0
WQ Output cell mass=0
WQ Output cell source sink temp=0
WQ Output nsm pathways=0
WQ Output nsm derived pathways=0
WQ Create Restart=0
WQ Fixed Restart=0
WQ System Summary=0
WQ Write To DSS=0
Sorting and Armoring Iterations= 10
XS Update Threshold= 0.02
Bed Roughness Predictor= 0
Hydraulics Update Threshold= 0.02
Energy Slope Method= 1
Volume Change Method= 1
Sediment Retention Method= 0
Sediment TS Multiplier= 1
Warm Up Method= 0
XS Weighting Method= 0
Number of US Weighted Cross Sections= 1
Number of DS Weighted Cross Sections= 1
Upstream XS Weight=0
Main XS Weight=1
Downstream XS Weight=0
Number of DS XS's Weighted with US Boundary= 1
Upstream Boundary Weight= 1
Weight of XSs Associated with US Boundary= 0
Number of US XS's Weighted with DS Boundary= 1
Downstream Boundary Weight= 0.5
Weight of XSs Associated with DS Boundary= 0.5
Percentile Method= 0
Sediment Output Level= 3
Mass or Volume Output= 0
Output Increment Type= 1
Profile and TS Output Increment= 1
Transport Output Increment 1
XS Output Flag= 0
XS Output Increment= 10
Read HDF5 Sediment Hotstart= 0
Sediment Hotstart Type= 0
Write Gradation File= 0
Read Gradation Hotstart= 0
Write HDF5 File= 1
Write Binary Output= 1
Write DSS Sediment File= 0
DSS Sediment Output Type= 1
SV Curve= 0
Specific Gage Flag= 0
Subcell Erosion Methods= 0
Subcell Deposition Methods= 0
Advection Scheme= 1
Matrix Solver= 0
Implicit Weighting Factor= 1
Maximum Outer Loop Convergence Iterations= 5
Convergence Maximum Absolute= 0.001
Convergence RMSE= 0.0001
Grain Fractions Max Abs Error= 0.001
Max Subgrid Regions= 1
Max Subgrid Length Scale= 3.402823E+38
Initial Layer Thickness= 3.402823E+38
Min Layer Thickness= 3.402823E+38
Max Layer Thickness= 3.402823E+38
Number of Layers= 5

--- SGRCMPRN.f01 (steady flow) ---

Flow Title=Flow
Program Version=6.10
Number of Profiles= 7
Profile Names=01pct,FW,10pct,04pct,02pct,0_2pct,01plus
River Rch & RM=SGRCMPRN,Main            ,13185
     552     552     291     387     467     771     816
River Rch & RM=SGRCMPRN,Main            ,9610
    1050    1050     566     744     890    1440    1550
River Rch & RM=SGRCMPRN,Main            ,6581
    1170    1170     636     834     997    1610    1730
River Rch & RM=SGRCMPRN,Main            ,6112
    1400    1400     765    1000    1190    1920    2070
River Rch & RM=SGRCMPRN,Main            ,0
    2880    2880    1620    2090    2470    3900    4260
Boundary for River Rch & Prof#=SGRCMPRN,Main            , 1
Up Type= 0
Dn Type= 1
Dn Known WS=2520.3
Boundary for River Rch & Prof#=SGRCMPRN,Main            , 2
Up Type= 0
Dn Type= 1
Dn Known WS=2521.3
Boundary for River Rch & Prof#=SGRCMPRN,Main            , 3
Up Type= 0
Dn Type= 1
Dn Known WS=2518.5
Boundary for River Rch & Prof#=SGRCMPRN,Main            , 4
Up Type= 0
Dn Type= 1
Dn Known WS=2519.3
Boundary for River Rch & Prof#=SGRCMPRN,Main            , 5
Up Type= 0
Dn Type= 1
Dn Known WS=2519.8
Boundary for River Rch & Prof#=SGRCMPRN,Main            , 6
Up Type= 0
Dn Type= 1
Dn Known WS=2521.4
Boundary for River Rch & Prof#=SGRCMPRN,Main            , 7
Up Type= 0
Dn Type= 1
Dn Known WS=2521.7
DSS Import GetInterval= 0
DSS Import GetPeak= 0
DSS Import FillOption= 0

--- SGRCMPRN.g01 (geometry) ---

Geom Title=Geometry
Program Version=6.10

River Reach=SGRCMPRN        ,Main
Reach XY= 30
 2293822.7702961470268.438414002 2292874.2152957470517.245332042
2291606.54891513470090.217033982 2290438.7940328470075.707876638
2290258.72910422469617.9830703142290374.03989722469483.361948475
2290403.01195213468645.590001971 2290176.5248723468250.144926727
2290316.78902747467981.9141639772290196.07404581467719.845134303
2290083.84297106467678.1411494762289976.77100672467356.388840228
2289557.15111105467151.621861309 2289168.9579898466763.417913318
2288874.94414213466703.3740701382288113.23731788466768.826343165
2287971.60999081466524.6411598922287820.65143571466548.396682795
2287717.66692914466267.039969057 2287408.3709598 466180.43285881
2287246.73086314 466280.798143642287231.75910831466104.271921888
2286960.82690738465868.555857897 2286875.3680888465835.183877394
2286778.61598572465912.8779477332286738.95399155465785.081943482
2286564.78701705465711.0929182322286367.10106072465764.152851477
 2286406.9300493465230.9961093962285765.46742147464639.195127651

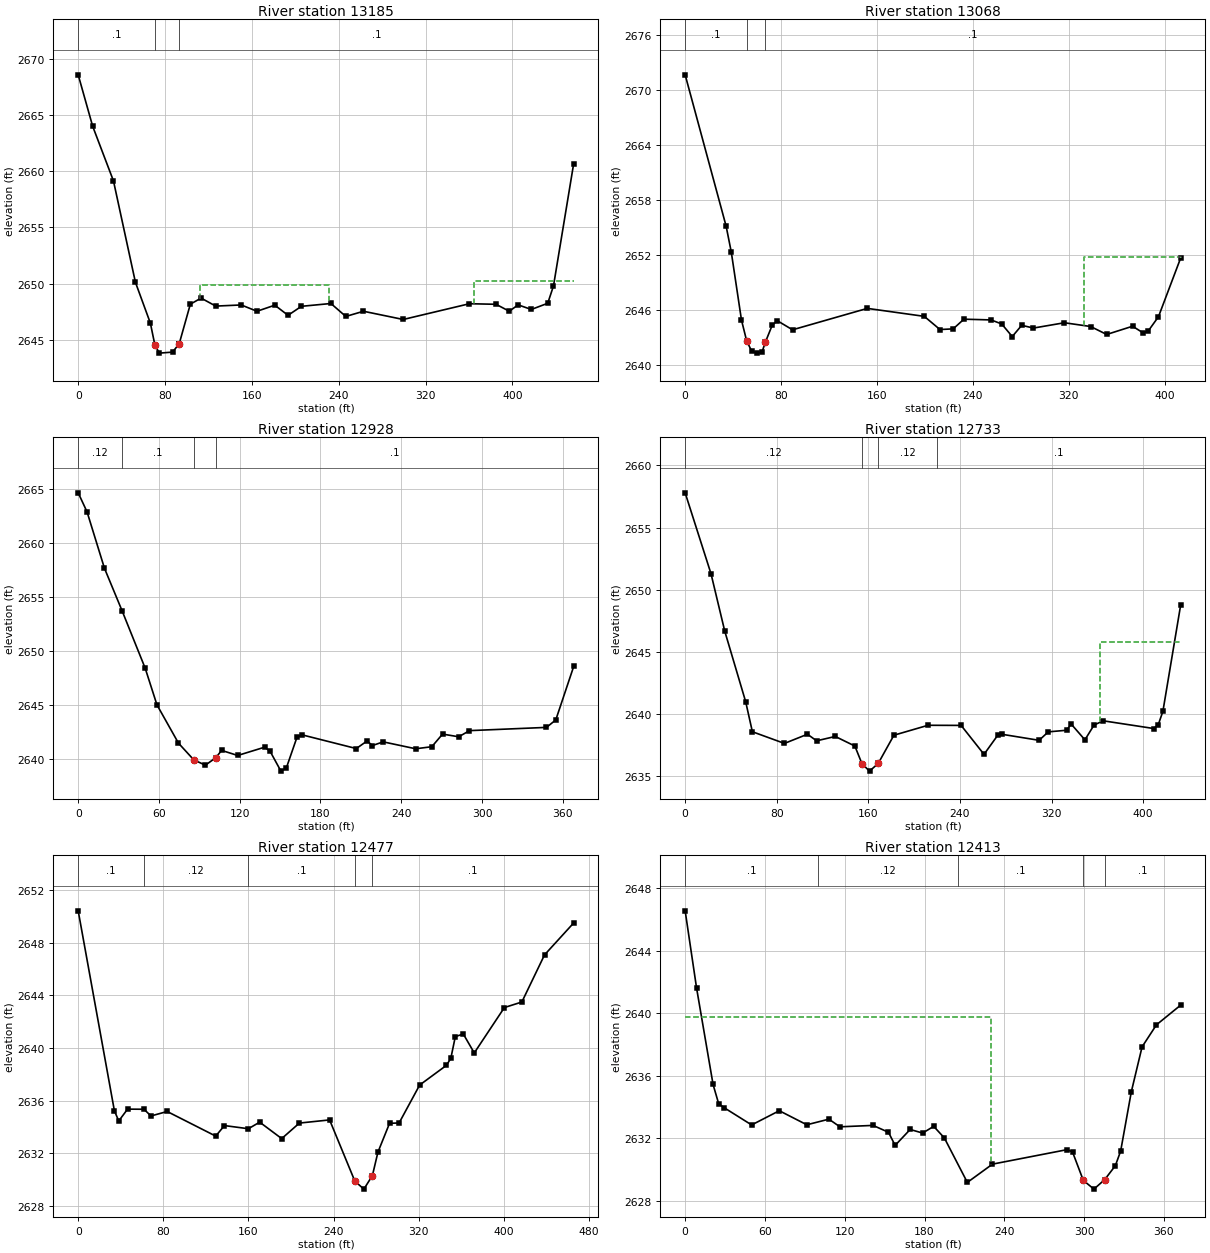
Type RM Length L Ch R = 1 ,13185   ,118.2,116.5,114.3
XS GIS Cut Line= 3
2293794.46993537470192.2210515332293843.79278452470419.701433413
 2293802.5486779470639.528269733
#Sta/Elev= 30
       0 2668.56    13.3    2664    32.5 2659.13    52.7 2650.13    66.5 2646.49
    70.6 2644.57    74.7 2643.83    86.9 2643.92    93.1 2644.67    93.1 2644.68
   103.3 2648.18   113.2 2648.72   126.7 2648.01   150.2 2648.11   164.7 2647.55
   181.1 2648.09   193.3 2647.19   205.6 2647.99   232.8 2648.24   246.5 2647.09
   262.8 2647.55   299.4 2646.82   360.4 2648.22   384.9 2648.17   397.1 2647.55
   405.2 2648.12   417.4 2647.71   432.5 2648.26   437.8  2649.8   456.4 2660.67
#Mann= 3 ,0,0
       0      .1       0    70.6    .045       0    93.1      .1       0
#XS Ineff= 2 ,-1
  112.16  230.72 2649.91  364.16  458.26 2650.27
Permanent Ineff=
       F       F
Bank Sta=70.6,93.1
XS Rating Curve= 0 ,0
Exp/Cntr(USF)=0,0
Exp/Cntr=0.3,0.1

Type RM Length L Ch R = 1 ,13068   ,133.2,140.5,153
XS GIS Cut Line= 4
2293676.91317871470237.1070373242293729.75308927470379.924227194
2293659.91346534470529.0890421452293623.22812355470618.225842936
#Sta/Elev= 30
       0 2671.68    34.2 2655.13    38.5  2652.3      47 2644.87    51.3 2642.61
    55.5 2641.47    59.8 2641.26    64.1 2641.37      67 2642.48    72.6  2644.3
    76.8 2644.81    89.6 2643.81     152 2646.15   199.5 2645.28   212.6 2643.84
   223.6 2643.91   232.6 2644.97   255.2 2644.89   264.1 2644.45   272.9 2643.07
   280.8  2644.3   290.6    2644   316.4 2644.58   338.3 2644.17   351.7  2643.3
   373.3  2644.2     382 2643.48   386.3 2643.67   394.9 2645.24   413.4 2651.65
#Mann= 3 ,0,0
       0      .1       0    51.3    .045       0      67      .1       0
#XS Ineff= 2 , 0
                          333.06         2651.78
Permanent Ineff=
       F       F
Bank Sta=51.3,67
XS Rating Curve= 0 ,0
Exp/Cntr(USF)=0,0
Exp/Cntr=0.3,0.1

Type RM Length L Ch R = 1 ,12928   ,189.8,194.8,175.5
XS GIS Cut Line= 3
2293588.66589507470255.1050399142293566.34708367470309.319947292
2293579.89404683470618.519287209
#Sta/Elev= 30
       0 2664.68     6.6 2662.91    19.5  2657.7    32.6 2653.76    49.8 2648.43
    58.5 2645.05    74.5  2641.5    85.9 2639.95    94.5 2639.46   102.4 2640.17
   106.5 2640.83   118.5 2640.36   138.6 2641.13   142.6 2640.74   150.6 2638.91
   154.6 2639.19   162.6 2642.07   166.6 2642.26   206.6    2641   214.6  2641.7
   218.6 2641.28   226.6 2641.62   250.7 2640.98   262.7 2641.17   270.7 2642.34
   282.7 2642.09   290.7 2642.66   347.9 2642.96   354.8 2643.65   368.1  2648.6
#Mann= 4 ,-1,0
       0     .12       0    32.6      .1       0    85.9    .045       0
   102.4      .1       0
Bank Sta=85.9,102.4
XS Rating Curve= 0 ,0
Exp/Cntr(USF)=0,0
Exp/Cntr=0.3,0.1

Type RM Length L Ch R = 1 ,12733   ,249.9,256.5,257
XS GIS Cut Line= 4
2293378.87513372470238.5961157862293386.28083891470364.000629625
 2293421.1469909470459.2447521322293411.55951928470664.674525395
#Sta/Elev= 30
       0  2657.8    22.6 2651.28    34.6 2646.66    52.9 2640.97    58.7 2638.57
    86.7 2637.63   106.8 2638.37   114.8 2637.84   131.1 2638.19   148.2 2637.42
   154.4    2636     161  2635.4   168.6 2636.02   182.3 2638.29   212.1 2639.09
     241 2639.08     261 2636.75     273 2638.29     277 2638.36   309.1 2637.88
   317.1 2638.56   333.1 2638.69   337.1 2639.19   349.1 2637.92   357.1 2639.11
   365.1 2639.45   409.2 2638.83   413.2 2639.15   417.2 2640.21   432.7 2648.76
#Mann= 4 ,-1,0
       0     .12       0   154.4    .045       0   168.6     .12       0
     220      .1       0
#XS Ineff= 2 , 0
                          362.13         2645.79
Permanent Ineff=
       F       F
Bank Sta=154.4,168.6
XS Rating Curve= 0 ,0
Exp/Cntr(USF)=0,0
Exp/Cntr=0.3,0.1

Type RM Length L Ch R = 1 ,12477   ,63.4,63.6,63.7
XS GIS Cut Line= 4
2293226.97736781470228.3636741762293171.71983952470436.227806376
2293182.73494221470536.9373167032293226.89274814470679.354759533
#Sta/Elev= 30
       0 2650.43      34 2635.24    38.1 2634.46    46.4 2635.36    61.8 2635.35
    68.4 2634.84    83.6 2635.18   129.2 2633.31   137.4 2634.11   159.9 2633.87
   170.5 2634.37   191.2 2633.12   207.8  2634.3   236.2 2634.54   259.9 2629.89
   268.4 2629.28   276.4 2630.31   281.6 2632.09   292.5 2634.28   301.5 2634.31
   320.8 2637.19     346 2638.69   350.1 2639.23   354.3 2640.87   361.8 2641.07
   372.1 2639.63   400.4 2643.08   416.8  2643.5   438.1 2647.08   465.5 2649.51
#Mann= 5 ,-1,0
       0      .1       0    61.8     .12       0   159.9      .1       0
   259.9    .045       0   276.4      .1       0
Bank Sta=259.9,276.4
XS Rating Curve= 0 ,0
Exp/Cntr(USF)=0,0
Exp/Cntr=0.3,0.1

Type RM Length L Ch R = 1 ,12413   ,234,236.4,231.6
XS GIS Cut Line= 3
2293151.78408955 470196.913179322293102.82508752 470375.37293417
2293120.69543339470562.018768799
#Sta/Elev= 30
       0 2646.57     8.6 2641.62      21 2635.45    25.2 2634.22    29.2 2633.97
      50 2632.86    70.8 2633.77    91.5 2632.87   108.1 2633.23   116.4 2632.74
   141.3 2632.83   152.9 2632.39   157.9 2631.55   169.2 2632.57   178.6 2632.34
   186.9 2632.77   194.9 2632.03   212.2 2629.18   231.1 2630.35   287.3 2631.28
   291.3 2631.13   299.4 2629.31   307.4 2628.75   315.5 2629.36   323.5 2630.25
   327.5 2631.19   335.5 2634.98   343.6 2637.86   354.4 2639.27   372.6 2640.53
#Mann= 5 ,-1,0
       0      .1       0     100     .12       0  205.05      .1       0
   299.4    .045       0   315.5      .1       0
#XS Ineff= 2 , 0
          230.12 2639.75
Permanent Ineff=
       F       F
Bank Sta=299.4,315.5
XS Rating Curve= 0 ,0
Exp/Cntr(USF)=0,0
Exp/Cntr=0.3,0.1

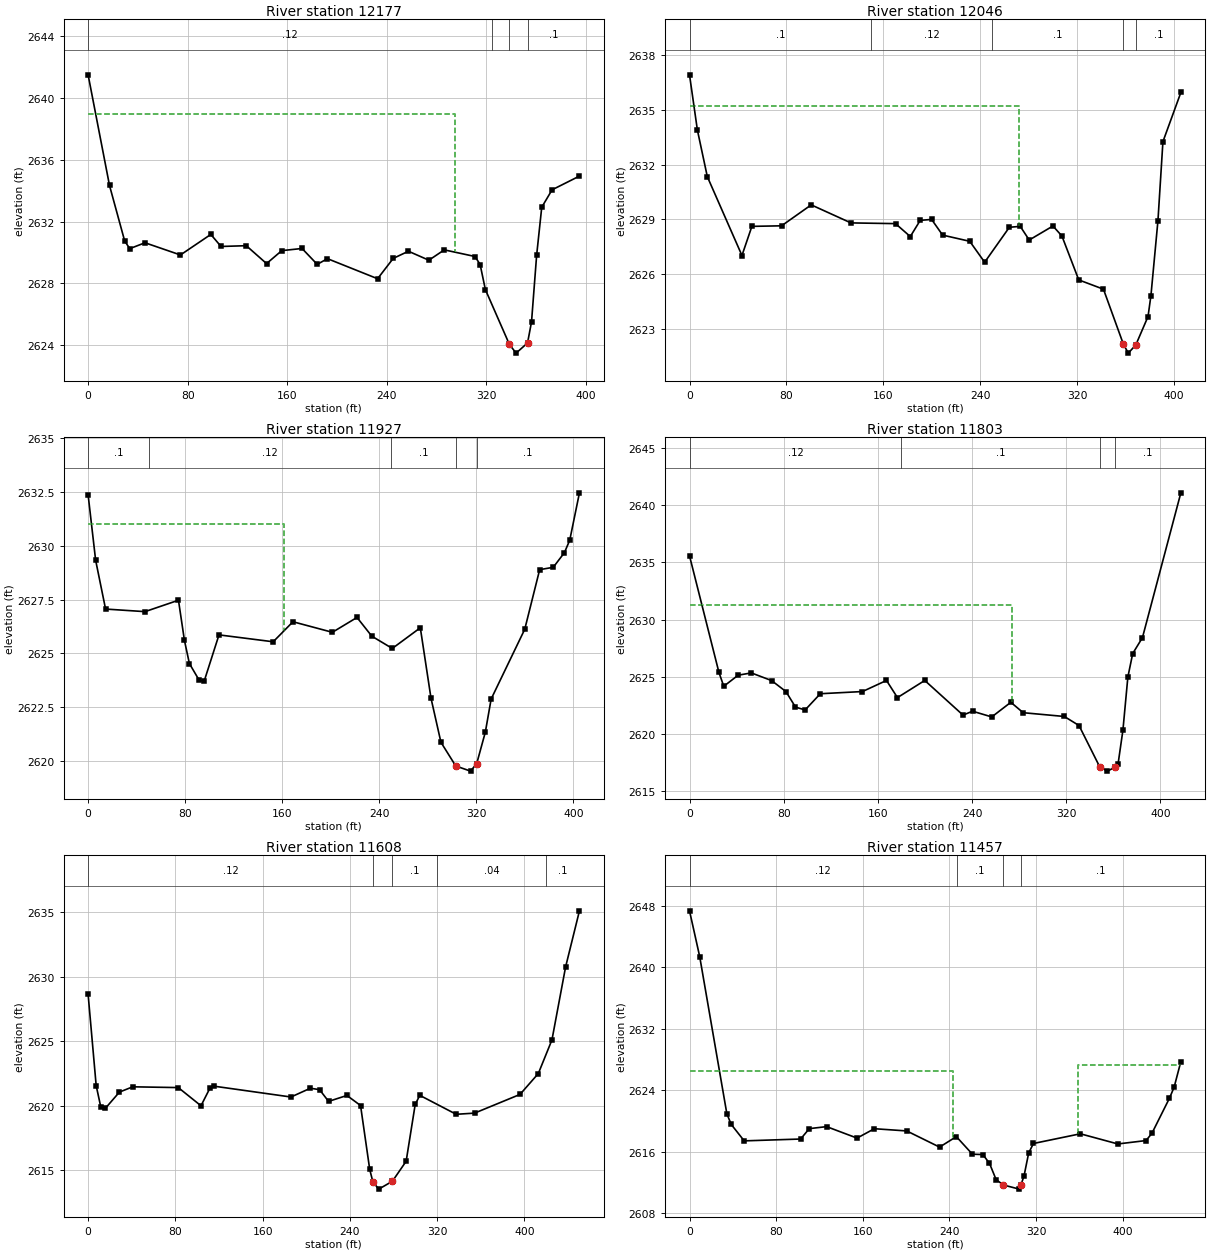
Type RM Length L Ch R = 1 ,12177   ,124.5,130.3,134.7
XS GIS Cut Line= 3
2292995.09475463470168.2761764532292945.84616457470428.390417911
2292977.42478127470554.548554938
#Sta/Elev= 30
       0 2641.51    17.2 2634.34    29.4 2630.74    33.5 2630.25    45.7 2630.63
    74.2 2629.84    98.6 2631.17   106.8 2630.39   127.1 2630.44   143.4 2629.28
   155.6 2630.12   171.9 2630.26   184.1 2629.23   192.3  2629.6   232.6  2628.3
   245.2 2629.62   257.4 2630.08   273.8  2629.5   286.2 2630.17   310.9 2629.74
     315 2629.22   319.2  2627.6  338.512624.046   343.9 2623.48   353.1 2624.14
   356.3 2625.51   360.4 2629.82   364.5 2632.93   372.8 2634.06   394.8 2634.95
#Mann= 4 ,-1,0
       0     .12       0  324.74      .1       0  338.51    .045       0
   353.1      .1       0
#XS Ineff= 2 , 0
          294.78 2638.98
Permanent Ineff=
       F       F
Bank Sta=338.51,353.1
XS Rating Curve= 0 ,0
Exp/Cntr(USF)=0,0
Exp/Cntr=0.3,0.1

Type RM Length L Ch R = 1 ,12046   ,119.6,119.2,116.6
XS GIS Cut Line= 2
2292913.80078935470150.8396058832292829.33155319470547.610700922
#Sta/Elev= 30
       0 2636.93     6.5  2633.9    14.7 2631.34    43.3 2627.01    51.5 2628.61
      76 2628.64   100.5 2629.79   133.3  2628.8   170.1 2628.76   182.3 2628.05
   190.5 2628.94   199.9 2628.99     209 2628.13   231.4 2627.79   243.7 2626.64
   264.1 2628.56   273.1 2628.61   280.5 2627.86   300.1 2628.63   307.5 2628.08
   321.4 2625.67   341.8 2625.16   358.2 2622.15   362.3 2621.65  368.51  2622.1
   378.6 2623.66     381 2624.81   386.8 2628.93   390.9 2633.26   405.7 2635.96
#Mann= 5 ,-1,0
       0      .1       0     150     .12       0     250      .1       0
   358.2    .045       0  368.51      .1       0
#XS Ineff= 2 , 0
          272.09  2635.2
Permanent Ineff=
       F       F
Bank Sta=358.2,368.51
XS Rating Curve= 0 ,0
Exp/Cntr(USF)=0,0
Exp/Cntr=0.3,0.1

Type RM Length L Ch R = 1 ,11927   ,124.3,124.4,124.6
XS GIS Cut Line= 3
2292792.71690441470147.0436851822292729.72690278470491.738642172
2292719.00469526470545.349679778
#Sta/Elev= 30
       0 2632.37     6.2 2629.33    14.4 2627.06    46.9 2626.94    74.5 2627.47
    79.4 2625.61    83.5 2624.53    91.6 2623.75    95.7 2623.71   107.9 2625.86
   152.6 2625.54   168.9 2626.47   201.4 2625.98   221.7 2626.67   233.9  2625.8
   250.8 2625.23   273.9 2626.19   282.7 2622.92   290.9 2620.87   303.1 2619.77
   315.3 2619.53   320.4 2619.88   327.5 2621.34   332.3 2622.88     360 2626.12
   372.3 2628.89   383.5    2629   392.7 2629.68   397.1 2630.26   405.1 2632.46
#Mann= 5 ,-1,0
       0      .1       0      50     .12       0     250      .1       0
   303.1    .045       0   320.4      .1       0
#XS Ineff= 2 , 0
           161.3    2631
Permanent Ineff=
       F       F
Bank Sta=303.1,320.4
XS Rating Curve= 0 ,0
Exp/Cntr(USF)=0,0
Exp/Cntr=0.3,0.1

Type RM Length L Ch R = 1 ,11803   ,196.1,194.2,194.5
XS GIS Cut Line= 3
2292684.48042135470120.5436323082292634.58569563470398.972186982
2292598.86308215470528.624218528
#Sta/Elev= 30
       0 2635.57      25 2625.37    29.1 2624.16    41.3 2625.13    52.5 2625.33
    69.7 2624.66    81.9  2623.7      90 2622.34    98.2 2622.09   111.1 2623.51
   146.9  2623.7   167.3 2624.67   176.6 2623.17   199.8 2624.67   232.3 2621.64
   240.4 2621.98   256.7 2621.48   272.9 2622.76   283.4 2621.85   318.3 2621.52
   330.8 2620.73348.42152617.108   354.9 2616.74   361.4 2617.08     364 2617.38
   368.1 2620.32   372.3 2624.97   376.4 2627.02   384.7 2628.42   417.3 2641.08
#Mann= 4 ,-1,0
       0     .12       0     180      .1       0348.4215    .045       0
   361.4      .1       0
#XS Ineff= 2 , 0
          273.59 2631.27
Permanent Ineff=
       F       F
Bank Sta=348.4215,361.4
XS Rating Curve= 0 ,0
Exp/Cntr(USF)=0,0
Exp/Cntr=0.3,0.1

Type RM Length L Ch R = 1 ,11608   ,152.3,151.5,154.5
XS GIS Cut Line= 2
 2292544.8439501470090.0587942252292414.56912872470521.268453001
#Sta/Elev= 30
       0 2628.65     7.4 2621.57    11.6 2619.93    15.8 2619.81    28.7 2621.07
    40.9 2621.48    82.7 2621.42   103.5 2620.01   111.9 2621.41   115.4 2621.53
     186 2620.69   203.8 2621.37   212.2 2621.26   220.5 2620.35   237.3 2620.81
   249.8 2620.03   258.2 2615.08   261.1 2614.11   266.5 2613.55     279 2614.16
   291.6 2615.71   299.9 2620.11   304.1 2620.82   337.5 2619.35   354.3 2619.44
     396 2620.89   412.8 2622.51   425.3 2625.12   437.8 2630.77   450.5 2635.12
#Mann= 5 ,-1,0
       0     .12       0   261.1    .045       0     279      .1       0
     320     .04       0     420      .1       0
Bank Sta=261.1,279
XS Rating Curve= 0 ,0
Exp/Cntr(USF)=0,0
Exp/Cntr=0.3,0.1

Type RM Length L Ch R = 1 ,11457   ,227.8,228.3,228.6
XS GIS Cut Line= 3
2292371.62794209470050.7379448862292361.18120417470227.382786192
2292254.81441801470482.853013671
#Sta/Elev= 30
       0 2647.32     9.4 2641.38    34.5 2620.94    38.5 2619.57    50.5 2617.43
   102.6 2617.67   110.6 2619.02   126.6 2619.28   154.7 2617.79   170.7 2619.01
   200.6 2618.72   230.9 2616.62   246.4 2617.98   261.2  2615.7   270.9 2615.65
     277 2614.51   283.1  2612.4   289.8  2611.7   304.5 2611.16  306.072611.719
   308.9 2612.88   313.2 2615.87   317.6 2617.09   360.9 2618.35   395.5 2617.03
   421.5 2617.47   426.9 2618.39   443.2 2622.98   447.5 2624.41   453.7 2627.73
#Mann= 4 ,-1,0
       0     .12       0  246.95      .1       0   289.8    .045       0
  306.07      .1       0
#XS Ineff= 2 , 0
          242.97  2626.5  358.43          2627.3
Permanent Ineff=
       F       F
Bank Sta=289.8,306.07
XS Rating Curve= 0 ,0
Exp/Cntr(USF)=0,0
Exp/Cntr=0.3,0.1

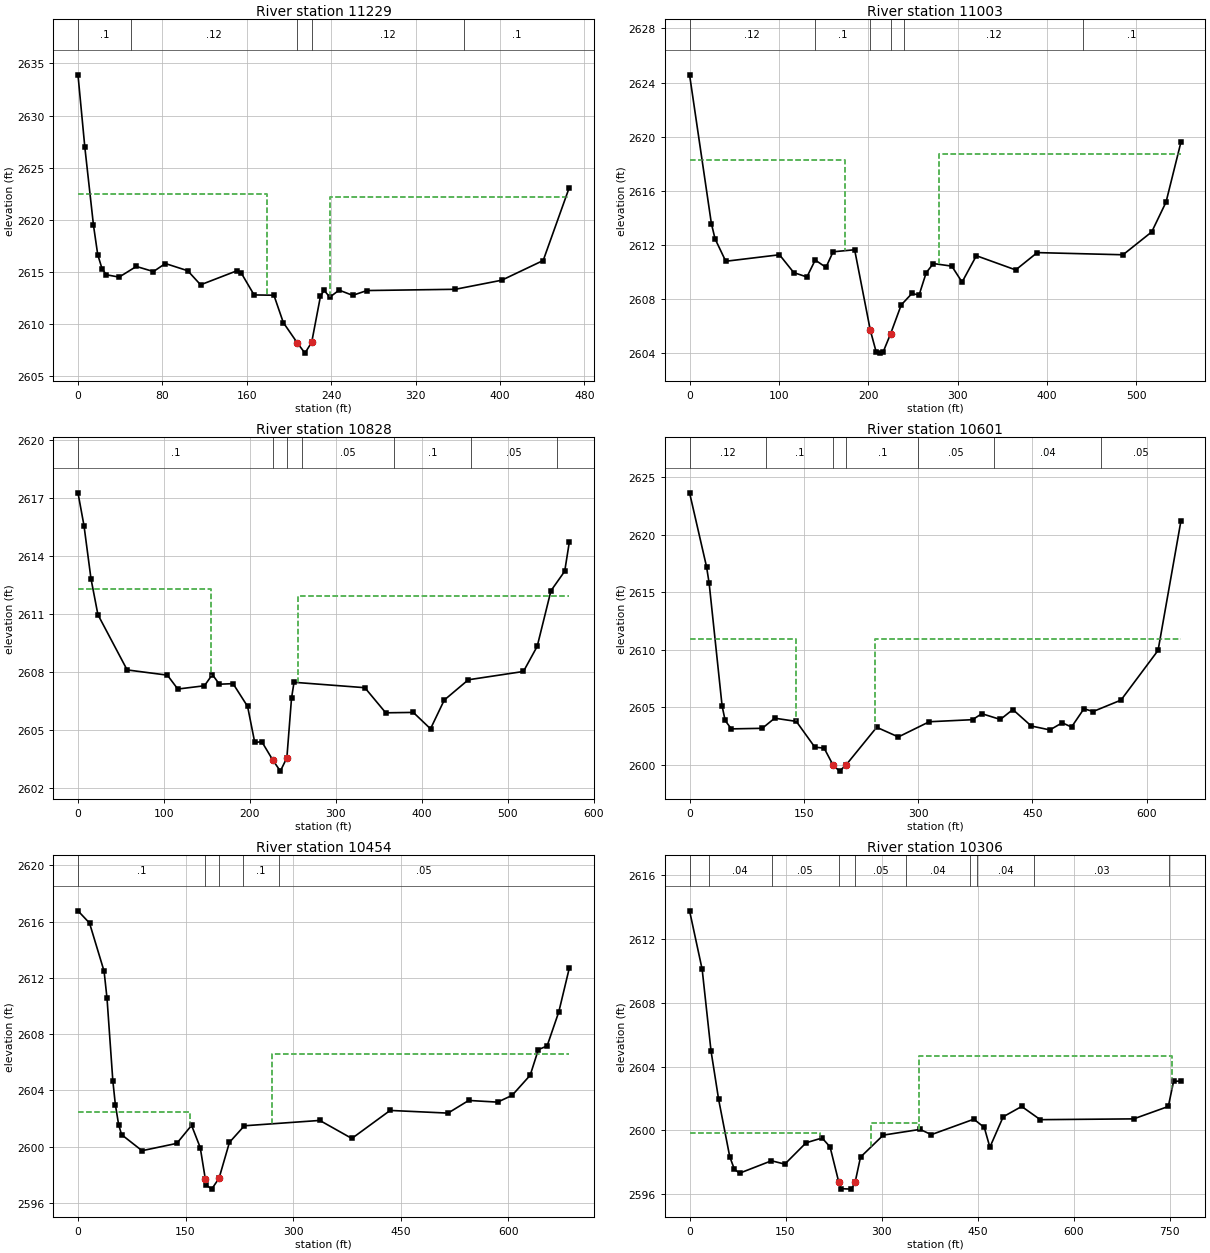
Type RM Length L Ch R = 1 ,11229   ,232.5,225.7,216.4
XS GIS Cut Line= 4
2292161.74348011470050.7379448862292139.32675973470177.245882169
2292043.43766453470383.8389047052292043.49729782470493.174364143
#Sta/Elev= 30
       0  2633.9     6.5 2626.95    14.7 2619.47    18.7 2616.67    22.8 2615.31
    26.9 2614.73      39 2614.51    55.3 2615.53    71.5 2615.04    82.8 2615.81
     104 2615.12   116.2 2613.77   150.5 2615.11   154.9 2614.87   166.9  2612.8
   185.7 2612.77   194.6 2610.15   207.8 2608.21   215.1 2607.22   221.5 2608.26
   229.8 2612.67   233.2 2613.24   238.7 2612.59   247.5 2613.26   260.3 2612.76
   273.9 2613.22   357.6 2613.34   401.6 2614.21   440.9  2616.1   465.6 2623.09
#Mann= 5 ,-1,0
       0      .1       0      50     .12       0   207.8    .045       0
   221.5     .12       0  366.24      .1       0
#XS Ineff= 2 , 0
          178.71 2622.48  238.96         2622.18
Permanent Ineff=
       F       F
Bank Sta=207.8,221.5
XS Rating Curve= 0 ,0
Exp/Cntr(USF)=0,0
Exp/Cntr=0.3,0.1

Type RM Length L Ch R = 1 ,11003   ,171.5,175.4,180.3
XS GIS Cut Line= 3
2291887.73412837469956.7667386782291907.27123967 470316.57276624
2291899.80143509470505.766117952
#Sta/Elev= 30
       0 2624.57    24.4 2613.58    28.5 2612.45    40.5 2610.79   100.6 2611.27
   116.6 2609.95   131.3 2609.63   140.6 2610.88   152.6 2610.34   160.6 2611.49
   184.7 2611.64   202.2  2605.7   208.7 2604.11   212.7    2604   216.7  2604.1
     225 2605.44   236.8 2607.56   248.8 2608.41   256.8 2608.29   264.8 2609.95
   272.8 2610.62   293.4 2610.43   304.9 2609.25   320.9  2611.2   364.9 2610.15
     389 2611.43     485 2611.27   517.1 2612.96   533.1 2615.16   549.7 2619.57
#Mann= 6 ,-1,0
       0     .12       0     140      .1       0   202.2    .045       0
     225      .1       0     240     .12       0  440.34      .1       0
#XS Ineff= 2 , 0
           174.1 2618.25  278.92         2618.75
Permanent Ineff=
       F       F
Bank Sta=202.2,225
XS Rating Curve= 0 ,0
Exp/Cntr(USF)=0,0
Exp/Cntr=0.3,0.1

Type RM Length L Ch R = 1 ,10828   ,233.1,226.6,220.9
XS GIS Cut Line= 4
2291714.62365217469938.2055208532291739.49551597470116.922980228
2291700.27902347470258.6728456252291710.52648738470502.446182966
#Sta/Elev= 30
       0 2617.28       7 2615.58    15.1 2612.84    23.2 2610.97    57.2 2608.11
     104 2607.84   116.1 2607.12   147.1 2607.29   156.3 2607.87   164.5 2607.37
   180.4  2607.4   197.3 2606.22   205.6 2604.36   213.9 2604.39   226.4 2603.46
   235.4 2602.87     243 2603.56   248.4 2606.64   251.3 2607.47   333.7 2607.19
     358 2605.89   390.1 2605.91   410.1 2605.06   426.1 2606.55   454.1  2607.6
   518.2 2608.03   534.2 2609.33   550.2 2612.21   566.2 2613.22   571.5 2614.71
#Mann= 7 ,-1,0
       0      .1       0   226.4    .045       0     243      .1       0
  260.44     .05       0  367.51      .1       0  457.51     .05       0
  557.51      .1       0
#XS Ineff= 2 , 0
          154.82 2612.32  255.42         2611.96
Permanent Ineff=
       F       F
Bank Sta=226.4,243
XS Rating Curve= 0 ,0
Exp/Cntr(USF)=0,0
Exp/Cntr=0.3,0.1

Type RM Length L Ch R = 1 ,10601   ,146.5,146.5,146
XS GIS Cut Line= 2
2291492.52542332469899.1340138592291601.56544881470534.614592565
#Sta/Elev= 30
       0 2623.64    22.3 2617.21    25.7 2615.78    42.7 2605.12    46.7 2603.86
    54.8 2603.13    95.4 2603.18   111.7 2604.06   140.1 2603.78   164.4 2601.54
   176.6 2601.46   188.5 2599.96   196.9 2599.46   205.8 2600.03   245.6 2603.27
     274 2602.43   314.6 2603.75   371.4 2603.93   383.6 2604.45   407.9 2603.95
   424.3 2604.81   448.5 2603.38   472.9 2603.04   489.1 2603.66   501.3 2603.29
   517.6 2604.88   529.7 2604.64   566.2 2605.63   614.9 2609.95   644.8 2621.16
#Mann= 7 ,-1,0
       0     .12       0     100      .1       0   188.5    .045       0
   205.8      .1       0     300     .05       0     400     .04       0
     540     .05       0
#XS Ineff= 2 , 0
          139.86  2610.9  243.17         2610.98
Permanent Ineff=
       F       F
Bank Sta=188.5,205.8
XS Rating Curve= 0 ,0
Exp/Cntr(USF)=0,0
Exp/Cntr=0.3,0.1

Type RM Length L Ch R = 1 ,10454   ,150.7,148.3,146.3
XS GIS Cut Line= 2
2291347.48958388469921.3374462032291469.04832759470595.542926527
#Sta/Elev= 30
       0 2616.76    16.1 2615.89    36.4 2612.47    40.5 2610.54    48.6 2604.69
    52.1    2603    56.7 2601.57    60.8 2600.86    89.3 2599.72   137.8 2600.24
   158.4 2601.52   170.5 2599.94   177.5 2597.73   178.7 2597.29   186.4 2596.99
   196.7 2597.76   211.2 2600.31     232 2601.49   337.2 2601.87   381.9 2600.59
   435.3 2602.58     516 2602.39   544.9 2603.29   585.1 2603.17   605.4 2603.65
   630.6 2605.08     642  2606.9   654.2 2607.16   670.5 2609.58   685.1 2612.68
#Mann= 5 ,-1,0
       0      .1       0   177.5    .045       0   196.7     .05       0
     230      .1       0     280     .05       0
#XS Ineff= 2 , 0
          155.81 2602.44  270.58         2606.56
Permanent Ineff=
       F       F
Bank Sta=177.5,196.7
XS Rating Curve= 0 ,0
Exp/Cntr(USF)=0,0
Exp/Cntr=0.5,0.3

Type RM Length L Ch R = 1 ,10306   ,61,61.3,61.5
XS GIS Cut Line= 3
2291199.40707521469872.1671258332291186.50986789469949.550369734
2291376.45055746470611.997836466
#Sta/Elev= 30
       0 2613.78    19.7  2610.1    33.5 2604.99    45.4 2601.94    62.8 2598.34
      70 2597.56    78.1 2597.31     128 2598.09   148.8 2597.88   182.1 2599.22
   207.1 2599.52   219.5 2598.96     233 2596.77   236.2 2596.34   252.8 2596.31
   258.6 2596.73   267.1 2598.32   302.6  2599.7   360.2 2600.06   377.7 2599.73
   444.2  2600.7   460.5 2600.18   469.2 2598.94     490 2600.85   518.9  2601.5
     548 2600.67   693.9 2600.72     748  2601.5   756.3 2603.08   767.6 2603.09
#Mann= 10 ,-1,0
       0     .05       0      30     .04       0  128.45     .05       0
     233    .045       0   258.6     .05       0  338.45     .04       0
  438.45     .05       0  448.45     .04       0  538.45     .03       0
  748.45     .04       0
#XS Ineff= 3 ,-1
    -9.3  203.542599.824  283.86  358.232600.441  358.23  753.41 2604.64
Permanent Ineff=
       F       F       F
Bank Sta=233,258.6
XS Rating Curve= 0 ,0
Exp/Cntr(USF)=0,0
Exp/Cntr=0.5,0.3

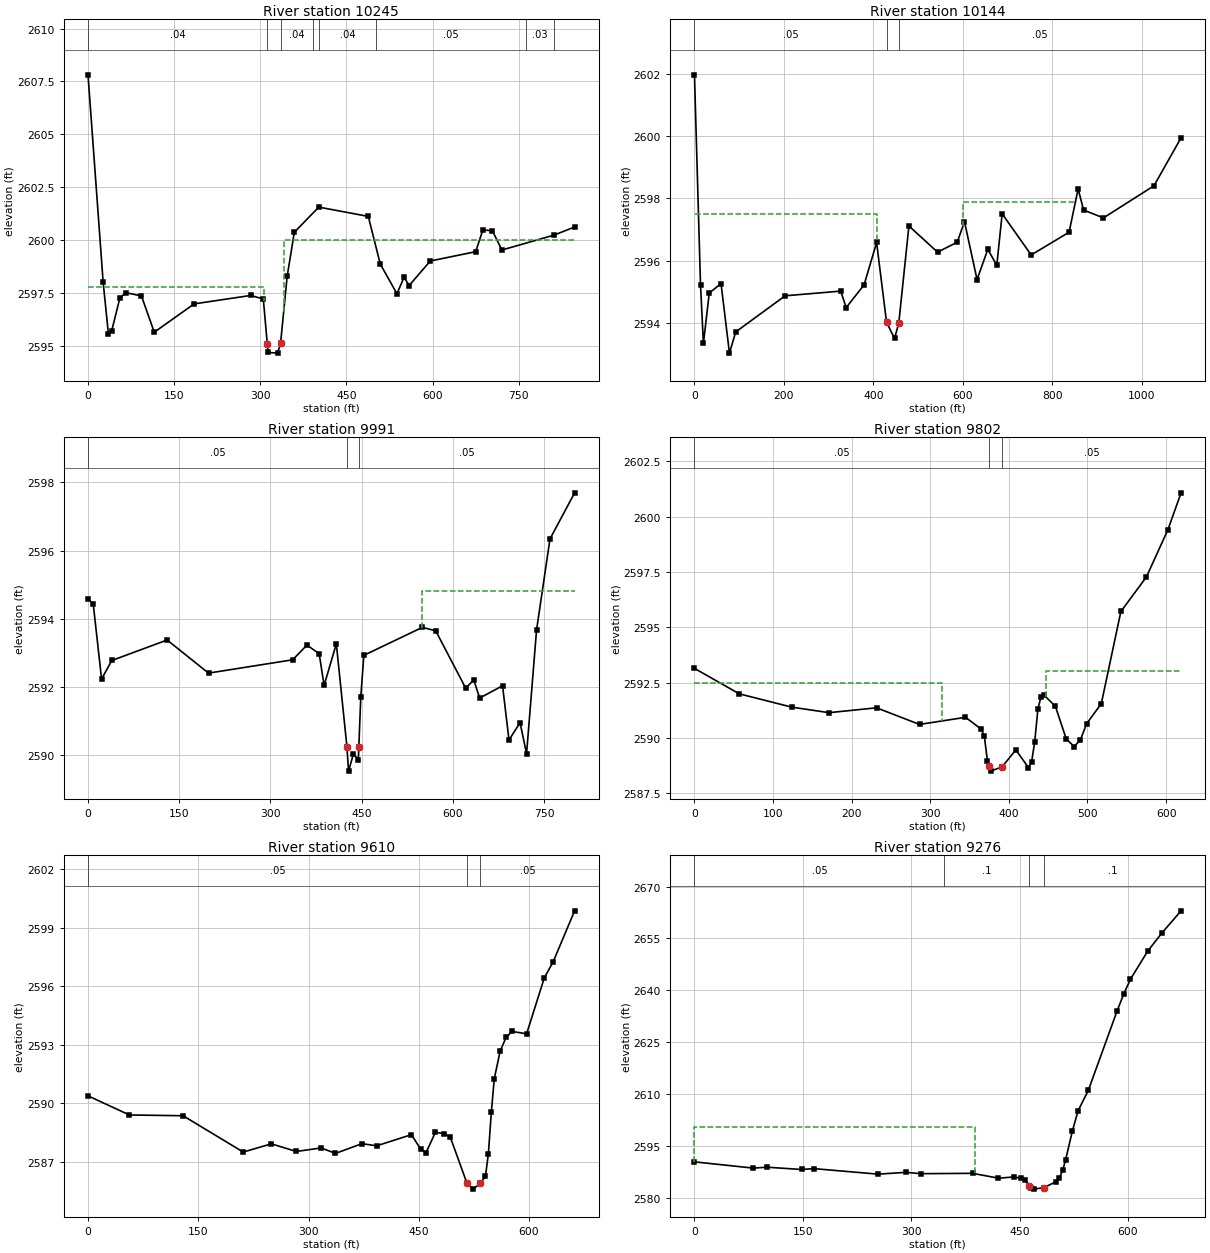
Type RM Length L Ch R = 1 ,10245   ,97.9,101.2,104.5
XS GIS Cut Line= 3
2291166.37065133469812.9538735012291117.45077207469924.938505383
2291313.81269346470623.066754766
#Sta/Elev= 30
       0 2607.81    26.4 2597.99    35.5 2595.56    41.3  2595.7    55.4 2597.24
    65.7  2597.5      93 2597.35   115.4 2595.63   184.8 2596.97   283.5 2597.37
   305.3  2597.2  312.282595.052   313.6 2594.67   330.2 2594.64   335.4 2595.12
   346.8 2598.27   359.3 2600.36   401.9 2601.55   488.1 2601.11   508.9 2598.86
     538 2597.45   550.4 2598.23   559.2 2597.84   596.1    2599   675.1 2599.44
   687.6 2600.47   704.2 2600.43   720.8 2599.52   812.2 2600.23   847.4 2600.61
#Mann= 8 ,-1,0
       0     .04       0  312.28    .045       0   335.4     .04       0
   392.2     .05       0   402.2     .04       0   502.2     .05       0
   762.2     .03       0   812.2     .04       0
#XS Ineff= 2 , 0
          305.65 2597.79  340.78            2600
Permanent Ineff=
       F       F
Bank Sta=312.28,335.4
XS Rating Curve= 0 ,0
Exp/Cntr=0.5,0.3

Type RM Length L Ch R = 1 ,10144   ,149,152.2,156.1
XS GIS Cut Line= 5
2291124.37364944469703.7049520622291050.62976072469799.630957718
2291087.17676762470371.5422277962291119.77274674470587.860998343
2291255.09544795470698.489775975
#Sta/Elev= 30
       0 2601.96    13.5 2595.23      20 2593.34    33.1 2594.96    59.4 2595.26
    78.2 2593.03    92.2 2593.71   202.7 2594.87     327 2595.02     339 2594.49
   379.1 2595.22   407.1 2596.58   429.3 2594.02   447.2  2593.5   456.7    2594
   479.3 2597.11   543.4 2596.27   587.3 2596.59   603.5 2597.25   631.6 2595.39
   655.6 2596.36   675.7 2595.85   687.7  2597.5   752.6 2596.18   837.3 2596.91
   857.5  2598.3   869.7 2597.62   914.1 2597.37    1027  2598.4  1087.6 2599.94
#Mann= 3 ,0,0
       0     .05       0   429.3    .045       0   456.7     .05       0
#XS Ineff= 2 ,-1
    2.03  406.982597.491  600.34  853.86 2597.89
Permanent Ineff=
       F       F
Bank Sta=429.3,456.7
XS Rating Curve= 0 ,0
Exp/Cntr(USF)=0,0
Exp/Cntr=0.3,0.1

Type RM Length L Ch R = 1 ,9991    ,191.2,190,189.5
XS GIS Cut Line= 5
2291077.83779435469703.322866427 2290944.9397678 469856.92086042
2290930.66469006470012.0892315522290909.98691485470216.799206147
 2290714.5819391470348.103078741
#Sta/Elev= 30
       0 2594.59     8.7 2594.42    22.3 2592.24    39.2 2592.78   130.1 2593.38
   198.2 2592.41   336.5  2592.8     360 2593.23   380.1 2592.98   388.2 2592.05
   408.3 2593.27   425.72590.258   428.4 2589.54   436.4 2590.04   444.5 2589.88
   445.32590.252   448.5  2591.7   453.5 2592.93   549.7 2593.75   571.7 2593.65
     621 2591.97   634.3 2592.21     644 2591.68   681.6 2592.04   692.2 2590.45
   710.4 2590.96   721.1 2590.05   737.5 2593.67   759.6 2596.34   800.1 2597.69
#Mann= 3 ,-1,0
       0     .05       0   425.7    .045       0   445.3     .05       0
#XS Ineff= 2 , 0
                          548.73         2594.81
Permanent Ineff=
       F       F
Bank Sta=425.7,445.3
XS Rating Curve= 0 ,0
Exp/Cntr(USF)=0,0
Exp/Cntr=0.3,0.1

Type RM Length L Ch R = 1 ,9802    ,192.2,191.7,191.5
XS GIS Cut Line= 4
2290984.71490964469793.892271361 2290739.5148317469990.878114217
2290736.44950506470119.2847588982290647.39846486470271.272943163
#Sta/Elev= 30
       0 2593.15    57.1    2592   123.8  2591.4   171.3 2591.15   231.6 2591.37
   286.3 2590.62   344.8 2590.94   364.8 2590.41   368.8 2590.08   372.8 2588.95
   374.9 2588.72   376.8 2588.51   391.3  2588.7   408.9 2589.47   424.9 2588.67
   428.9 2588.92   432.9 2589.83   436.9 2591.31   440.9 2591.87   445.2 2591.93
   459.3 2591.43     473 2589.96   483.1 2589.62     491 2589.92   498.9 2590.65
   517.6 2591.56   542.5 2595.72     575 2597.28   602.4 2599.42   619.1 2601.08
#Mann= 3 ,0,0
       0     .05       0   374.9    .045       0   391.3     .05       0
#XS Ineff= 2 , 0
           315.1 2592.48  446.82         2593.05
Permanent Ineff=
       F       F
Bank Sta=374.9,391.3
XS Rating Curve= 0 ,0
Exp/Cntr(USF)=0,0
Exp/Cntr=0.3,0.1

Type RM Length L Ch R = 1 ,9610    ,316.8,334.3,343.3
XS GIS Cut Line= 3
2290827.73600584 469793.892287432290547.86147666469840.128992387
2290546.87371972470218.439901609
#Sta/Elev= 30
       0 2590.38    56.3  2589.4   129.3 2589.36   211.2  2587.5   249.5 2587.92
   283.4 2587.53   317.1 2587.71   336.7 2587.43   372.7 2587.93   392.7 2587.82
     440 2588.39   452.7 2587.64   459.9 2587.47   472.7 2588.52   484.7 2588.43
   492.7 2588.28   515.32585.928   523.8  2585.6   533.72585.893   540.7 2586.26
   544.7 2587.42   548.7 2589.54   552.7 2591.26   560.7 2592.67   568.7 2593.37
   576.7 2593.68   596.7 2593.56   620.7 2596.42   632.7 2597.24     662 2599.86
#Mann= 3 ,0,0
       0     .05       0   515.3    .045       0   533.7     .05       0
Bank Sta=515.3,533.7
XS Rating Curve= 0 ,0
Exp/Cntr(USF)=0,0
Exp/Cntr=0.3,0.1

Type RM Length L Ch R = 1 ,9276    ,118.6,118.1,117.2
XS GIS Cut Line= 4
2290818.00747818469780.5429962822290649.79135499469729.175140942
2290458.96434257469828.1901147482290204.64536597469951.193422158
#Sta/Elev= 30
       0 2590.34    81.4 2588.53   100.3 2588.79   148.5 2588.13     165 2588.39
   254.1 2586.78   292.8 2587.31   312.9 2586.92   384.8 2587.02   420.7 2585.62
   441.6 2585.96   451.7 2585.62   457.4 2585.19463.56012583.484   465.6 2582.86
   469.5 2582.45483.56012582.877   500.6 2584.63   505.1 2585.77   509.5 2587.87
   513.5 2590.82   522.8 2599.13   530.9 2605.16     545 2611.02     585 2634.09
   593.9 2638.83   603.3 2643.17   627.3 2651.34   647.2 2656.64   673.4 2662.97
#Mann= 4 ,-1,0
       0     .05       0  345.88      .1       0463.5601    .045       0
483.5601      .1       0
#XS Ineff= 2 , 0
          387.95  2600.5
Permanent Ineff=
       F       F
Bank Sta=463.5601,483.5601
XS Rating Curve= 0 ,0
Exp/Cntr(USF)=0,0
Exp/Cntr=0.3,0.1