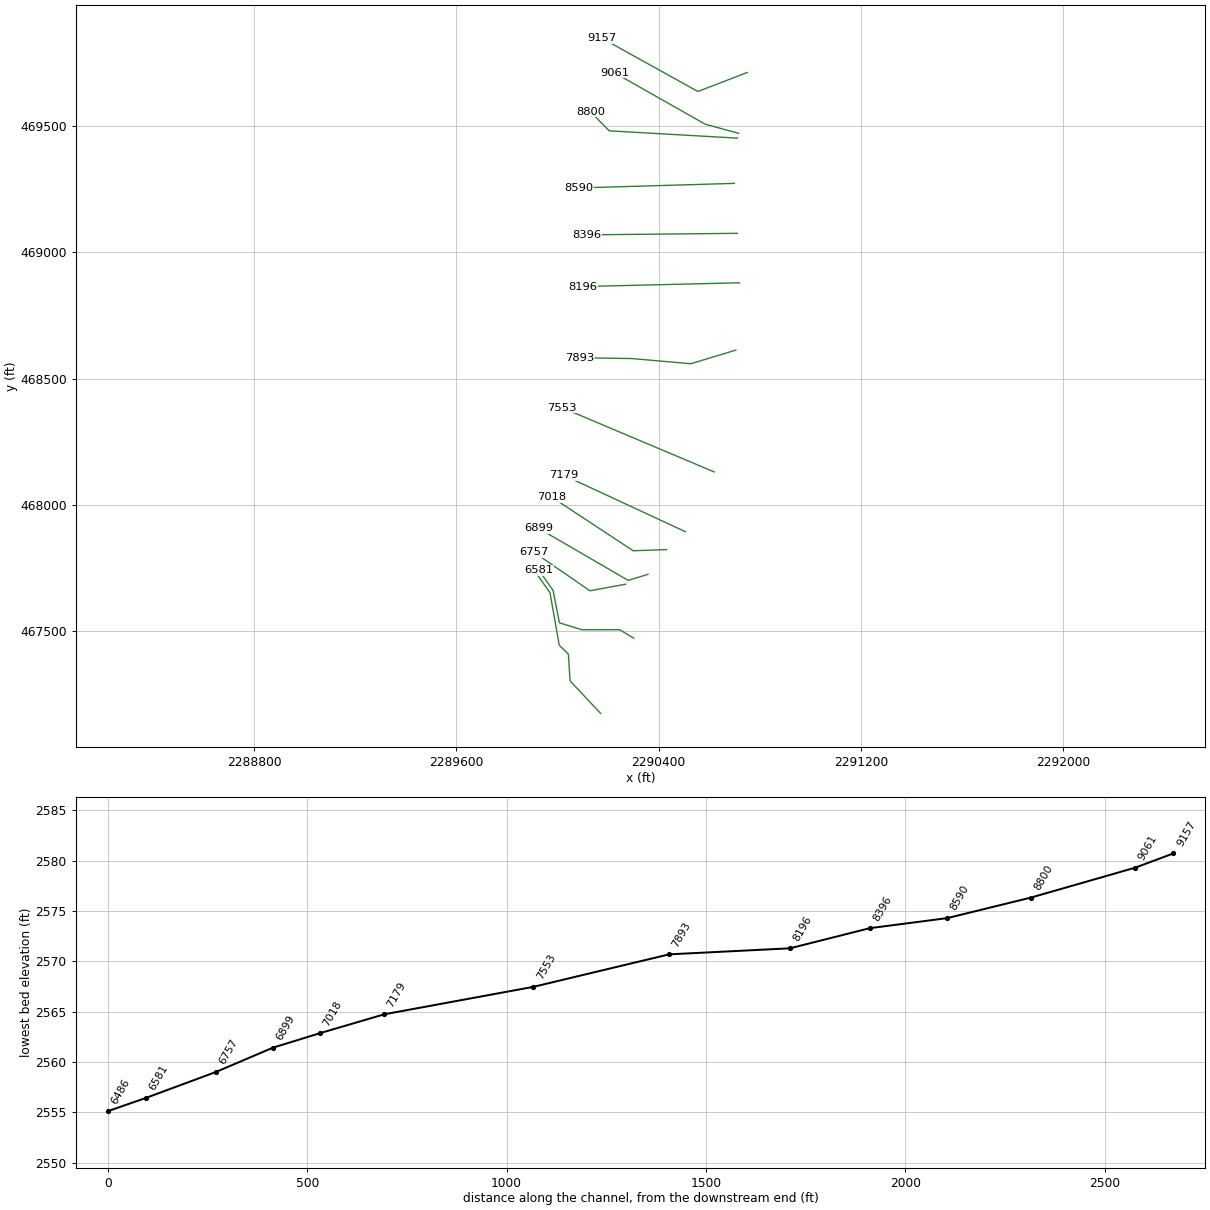
HEC-RAS study SGRCMPRN.prj: SGRCMPRN

--- SGRCMPRN.g01 (geometry) --- (continued)

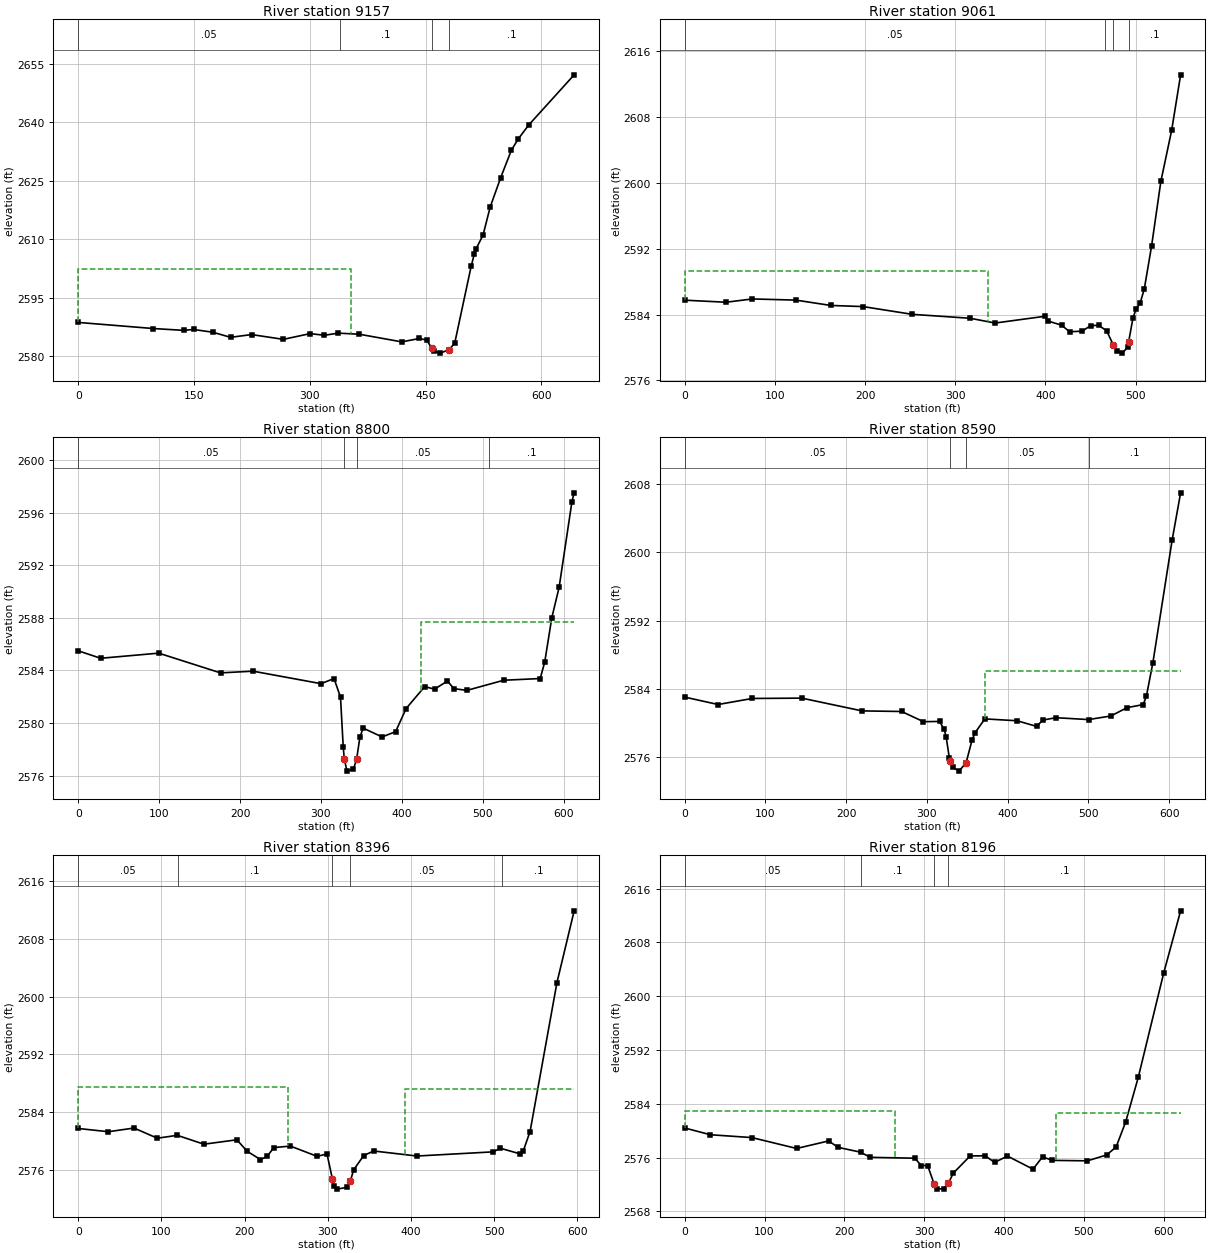
Type RM Length L Ch R = 1 ,9157    ,96.2,96.1,96
XS GIS Cut Line= 3
 2290751.0707668469710.9603700372290555.66579105469635.589879389
2290176.95233804469845.882853293
#Sta/Elev= 30
       0 2588.62    97.4 2587.05   136.7 2586.58   149.4 2586.81   174.6 2586.09
   197.4 2584.79   224.6  2585.5   265.8 2584.27   300.4 2585.74   319.1 2585.32
     337 2585.87   364.4 2585.58   419.3 2583.62   442.2  2584.5   451.7 2584.07
457.97282582.013   461.2  2581.2   469.1 2580.73   480.9 2581.66   487.9 2583.35
   509.3 2603.18   513.2 2606.17   515.4 2607.48   524.6  2611.1   533.8 2618.28
   547.4 2625.82   561.2 2632.85   570.3 2635.82   583.8 2639.37   642.6 2652.25
#Mann= 4 ,-1,0
       0     .05       0  339.44      .1       0457.9728    .045       0
   480.9      .1       0
#XS Ineff= 2 , 0
          353.51  2602.4
Permanent Ineff=
       F       F
Bank Sta=457.9728,480.9
XS Rating Curve= 0 ,0
Exp/Cntr(USF)=0,0
Exp/Cntr=0.3,0.1

Type RM Length L Ch R = 1 ,9061    ,255.2,261.2,268.7
XS GIS Cut Line= 3
2290716.55614635469470.3456430792290584.79794467469506.131980526
2290225.13212862469710.085855264
#Sta/Elev= 30
       0 2585.75      46  2585.5      75  2585.9   123.2 2585.76     162 2585.11
   197.9 2584.97   252.2 2584.03   316.6 2583.55   344.2 2582.97   399.4 2583.79
   403.3  2583.2     418 2582.71   426.9 2581.91   440.7 2581.98   450.3 2582.66
   459.1 2582.69   467.9 2582.03   475.2 2580.35   479.6 2579.51   485.5 2579.31
   491.4 2580.07  492.252580.618   497.2 2583.61   500.5 2584.63   505.1  2585.4
   509.7 2587.11   517.8 2592.34   528.1 2600.21   540.1 2606.43     550 2613.16
#Mann= 4 ,-1,0
       0     .05       0  466.53      .1       0   475.2    .045       0
  492.25      .1       0
#XS Ineff= 2 , 0
          336.88 2589.34
Permanent Ineff=
       F       F
Bank Sta=475.2,492.25
XS Rating Curve= 0 ,0
Exp/Cntr(USF)=0,0
Exp/Cntr=0.3,0.1

Type RM Length L Ch R = 1 ,8800    ,208.6,209.9,211.1
XS GIS Cut Line= 3
2290711.82446556469451.2045818872290205.09616608469479.984244952
2290131.11700061469555.093235131
#Sta/Elev= 30
       0 2585.49    27.7 2584.92    99.5 2585.31   175.9 2583.81     216 2583.94
   300.1 2582.99   316.2 2583.38   324.2 2581.96   327.6 2578.14   328.9 2577.27
   332.2 2576.34   340.2 2576.48   344.2 2577.28   348.2 2578.93   352.2 2579.61
   375.6 2578.94   392.3 2579.34   405.3  2581.1   428.3 2582.77   440.4 2582.57
   456.4 2583.19   464.4 2582.61   480.4 2582.48     526 2583.25     571 2583.38
   576.6 2584.62   585.4 2588.01   594.4 2590.31   610.3 2596.84     613  2597.5
#Mann= 4 ,-1,0
       0     .05       0   328.9    .045       0   344.2     .05       0
  507.54      .1       0
#XS Ineff= 2 , 0
                           423.8         2587.68
Permanent Ineff=
       F       F
Bank Sta=328.9,344.2
XS Rating Curve= 0 ,0
Exp/Cntr(USF)=0,0
Exp/Cntr=0.3,0.1

Type RM Length L Ch R = 1 ,8590    ,195,194.1,193.9
XS GIS Cut Line= 2
2290699.82571401469272.155347276 2290085.8359294 469254.17469063
#Sta/Elev= 30
       0    2583    41.4 2582.13    83.7 2582.84     145 2582.88   219.7 2581.38
   268.7 2581.31   295.8 2580.11   315.8 2580.14   321.4  2579.2   323.8 2578.36
   327.8 2575.86   329.1 2575.49   331.8 2574.76   339.8  2574.3   348.6 2575.28
   355.8  2577.9   359.3 2578.76   371.8 2580.44   411.8 2580.22   435.8 2579.56
   443.8  2580.3   459.8 2580.58   500.2 2580.36   527.9 2580.78   547.9 2581.76
   567.9 2582.12   571.9 2583.11   579.9 2587.02   603.9 2601.52   614.3 2607.01
#Mann= 4 ,-1,0
       0     .05       0   329.1    .045       0   348.6     .05       0
   500.2      .1       0
#XS Ineff= 2 , 0
                          372.49          2586.1
Permanent Ineff=
       F       F
Bank Sta=329.1,348.6
XS Rating Curve= 0 ,0
Exp/Cntr(USF)=0,0
Exp/Cntr=0.3,0.1

Type RM Length L Ch R = 1 ,8396    ,200,200.2,214
XS GIS Cut Line= 2
2290711.30891437469074.6597382512290115.11623775469068.607020722
#Sta/Elev= 30
       0 2581.71    36.2 2581.26    67.1 2581.77    95.1 2580.36   119.1 2580.76
   151.1 2579.53   190.7 2580.14   203.1 2578.55   219.1  2577.4   227.1 2577.83
   235.1 2579.06   255.1 2579.27   287.1 2577.85   299.1 2578.17   305.5 2574.75
   307.1 2573.74   311.2  2573.3   323.2 2573.55   327.2 2574.45   331.2 2575.99
   343.2 2577.95   355.2 2578.59   407.2 2577.89   499.2 2578.47   507.2 2578.98
   531.2 2578.19   535.1 2578.62   543.2 2581.28   575.5 2601.93   596.2 2611.89
#Mann= 5 ,-1,0
       0     .05       0     120      .1       0   305.5    .045       0
   327.2     .05       0     510      .1       0
#XS Ineff= 2 , 0
          251.81  2587.5  392.77         2587.25
Permanent Ineff=
       F       F
Bank Sta=305.5,327.2
XS Rating Curve= 0 ,0
Exp/Cntr(USF)=0,0
Exp/Cntr=0.3,0.1

Type RM Length L Ch R = 1 ,8196    ,303.2,302.8,295.1
XS GIS Cut Line= 2
2290720.38396581468878.9581664042290099.36125633468864.229771073
#Sta/Elev= 30
       0  2580.4    32.2 2579.39    84.2 2578.97   140.2 2577.35   180.3 2578.47
   192.3 2577.51   220.3  2576.8   232.3 2576.03   288.3  2575.9   296.3 2574.81
   304.3 2574.81   312.3 2572.13   316.3  2571.3   324.3 2571.38   330.4 2572.16
   336.3 2573.66   357.6 2576.24   376.3 2576.26   388.3 2575.28   404.3 2576.22
   436.3 2574.27   448.3 2576.11   460.3 2575.58   504.4 2575.51   528.4 2576.38
   540.4 2577.57   552.4 2581.31   568.1 2587.91   599.9 2603.41   621.2 2612.71
#Mann= 4 ,-1,0
       0     .05       0   220.3      .1       0   312.3    .045       0
   330.4      .1       0
#XS Ineff= 2 , 0
          262.85 2582.88  465.12         2582.56
Permanent Ineff=
       F       F
Bank Sta=312.3,330.4
XS Rating Curve= 0 ,0
Exp/Cntr(USF)=0,0
Exp/Cntr=0.3,0.1

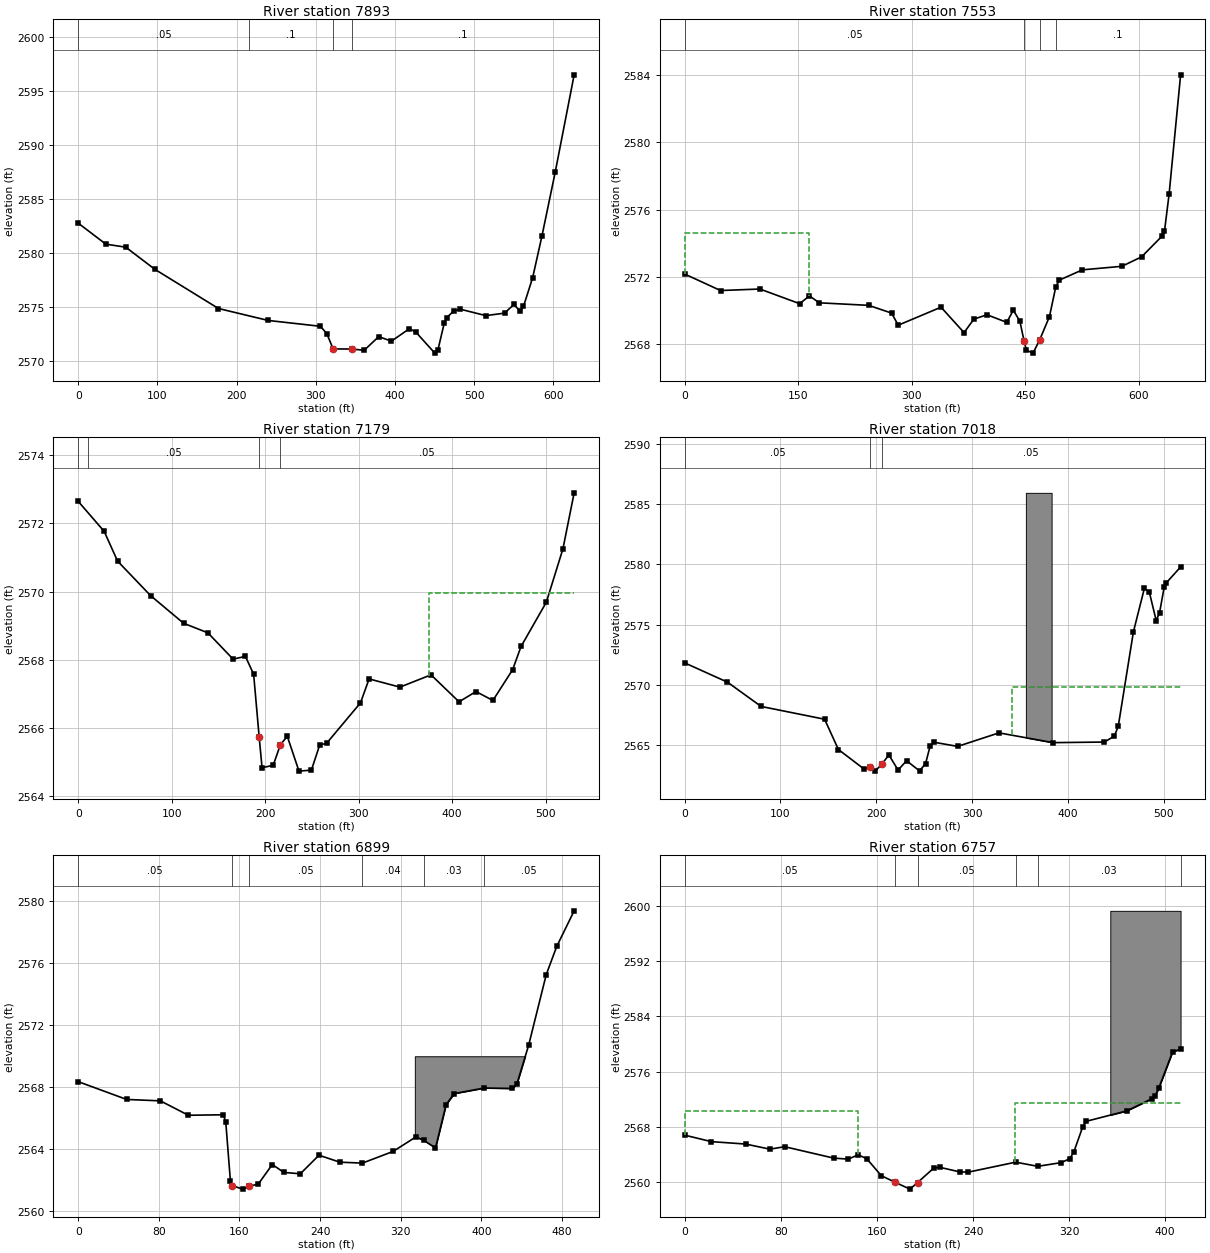
Type RM Length L Ch R = 1 ,7893    ,349.4,340.4,282.8
XS GIS Cut Line= 4
2290705.55234472468612.7068802132290527.94955377468558.817209526
 2290294.2791551468579.3402335392290088.19677654468582.392221606
#Sta/Elev= 30
       0 2582.76    34.9 2580.81      60 2580.53    96.9 2578.47   177.1 2574.84
     240 2573.73   305.8 2573.19   313.9 2572.52   321.9 2571.09   345.6 2571.08
   361.1 2570.96   379.5 2572.23   395.5 2571.81   418.3 2572.97   426.3 2572.66
   450.3  2570.7   454.3 2571.01   462.3  2573.5   465.1 2573.98   474.3 2574.61
   482.3 2574.78   514.7 2574.18   538.4 2574.41   550.3 2575.22   558.1 2574.57
   562.3 2575.03   573.9  2577.7   585.7 2581.59   602.3 2587.46   626.3 2596.52
#Mann= 4 ,-1,0
       0     .05       0   215.6      .1       0   321.9    .045       0
   345.6      .1       0
Bank Sta=321.9,345.6
XS Rating Curve= 0 ,0
Exp/Cntr(USF)=0,0
Exp/Cntr=0.3,0.1

Type RM Length L Ch R = 1 ,7553    ,257.9,374.1,287.4
XS GIS Cut Line= 2
2290619.99361675 468130.925852092290016.68899704468385.593942129
#Sta/Elev= 30
       0 2572.17    47.4 2571.19    99.3 2571.28   151.8 2570.41   164.8 2570.87
   177.8 2570.46   242.9 2570.31   273.2 2569.85     282 2569.13   338.5  2570.2
   368.9 2568.69   381.9 2569.49   399.2 2569.75   425.3  2569.3     434 2570.02
   442.7 2569.36   448.1  2568.2   451.3 2567.64     460 2567.47   468.7 2568.25
   481.7 2569.64   490.1 2571.42   494.8 2571.81   525.2 2572.42   577.3 2572.63
   603.3 2573.19   630.5 2574.43   633.6 2574.72   639.7 2576.92   654.9 2584.01
#Mann= 4 ,-1,0
       0     .05       0   448.1    .045       0   468.7     .05       0
     490      .1       0
#XS Ineff= 2 , 0
          163.95 2574.63
Permanent Ineff=
       F       F
Bank Sta=448.1,468.7
XS Rating Curve= 0 ,0
Exp/Cntr(USF)=0,0
Exp/Cntr=0.3,0.1

Type RM Length L Ch R = 1 ,7179    ,151,160.7,130.6
XS GIS Cut Line= 2
2290506.35662016467894.3892248692290025.28817986468117.709197155
#Sta/Elev= 30
       0 2572.64    27.8 2571.76    42.1 2570.89    77.4 2569.88   112.7 2569.07
   138.7 2568.79   165.6 2568.02   178.8  2568.1   187.6 2567.58   193.5 2565.75
   196.6 2564.84   208.5 2564.91   216.32565.516   223.6 2565.76   236.1 2564.74
   249.4 2564.77   258.2  2565.5   265.8 2565.56   301.9 2566.74   311.1 2567.44
   344.1  2567.2   377.3 2567.56   407.3 2566.77   425.4 2567.07   443.5 2566.81
   464.6 2567.71   473.6 2568.39   500.7 2569.69   518.4 2571.25   530.4 2572.89
#Mann= 4 ,-1,0
       0     .04       0      10     .05       0   193.5    .045       0
   216.3     .05       0
#XS Ineff= 2 , 0
                           374.7         2569.95
Permanent Ineff=
       F       F
Bank Sta=193.5,216.3
XS Rating Curve= 0 ,0
Exp/Cntr(USF)=0,0
Exp/Cntr=0.3,0.1

Type RM Length L Ch R = 1 ,7018    ,113.6,118.6,121.3
XS GIS Cut Line= 3
 2290431.9166294467823.6712336452290299.78564579467819.018734222
2289977.83268575468031.172707894
#Sta/Elev= 30
       0 2571.84    44.7 2570.24    79.8 2568.23   146.1 2567.17   160.5 2564.66
     187 2563.06     194 2563.25   198.8 2562.87   205.7 2563.43   213.2 2564.21
   222.8 2562.96   231.7 2563.73   245.2 2562.89   251.5 2563.49   256.3 2564.96
   260.5 2565.26     285 2564.92   328.2 2566.04   384.7 2565.23   438.3 2565.28
   448.7 2565.78   452.7 2566.59   468.5 2574.41     480 2578.03   485.1 2577.71
   492.3 2575.35   495.8 2575.99   500.6  2578.1   502.5 2578.44   517.8 2579.79
#Mann= 3 ,-1,0
       0     .05       0     194    .045       0   205.7     .05       0
#XS Ineff= 2 , 0
                          342.17         2569.88
Permanent Ineff=
       F       F
#Block Obstruct= 1 ,-1
  356.23  383.11 2585.93
Bank Sta=194,205.7
XS Rating Curve= 0 ,0
Exp/Cntr(USF)=0,0
Exp/Cntr=0.3,0.1

Type RM Length L Ch R = 1 ,6899    ,116.2,142.6,103.3
XS GIS Cut Line= 3
2290358.10836917467725.8695616712290280.24514822467701.775748772
2289925.19099094467908.028967937
#Sta/Elev= 30
       0 2568.36    48.1 2567.21    81.5 2567.12   109.3 2566.19     144 2566.22
   146.4 2565.76     151 2561.96152.62012561.653   163.1 2561.42169.32012561.597
   178.7 2561.75   192.6 2563.01     204  2562.5   220.4 2562.41   238.9 2563.61
   259.6 2563.16     282  2563.1   312.3 2563.85   335.1 2564.79   343.1 2564.56
   354.5 2564.08     365 2566.87     373 2567.59     403 2567.95   430.7 2567.92
   435.2  2568.2   446.9  2570.7   464.4 2575.27   474.8 2577.09   492.1 2579.39
#Mann= 6 ,-1,0
       0     .05       0152.6201    .045       0169.3201     .05       0
     282     .04       0   343.1     .03       0     403     .05       0
#Block Obstruct= 1 ,-1
     334     452    2570
Bank Sta=152.6201,169.3201
XS Rating Curve= 0 ,0
Exp/Cntr(USF)=0,0
Exp/Cntr=0.3,0.1

Type RM Length L Ch R = 1 ,6757    ,161.6,175.7,196.9
BEGIN DESCRIPTION:
IFAs set to uncross profile at xs 6899
END DESCRIPTION:
XS GIS Cut Line= 3
2290270.00964949467686.8877506192290128.57366704467660.833753853
2289907.11469452467813.435734915
#Sta/Elev= 30
       0 2566.82    22.2 2565.88    50.7 2565.53      71 2564.79    83.2 2565.15
   123.9  2563.5   136.1 2563.35   144.4 2563.97   151.5 2563.42   163.7 2560.95
   175.3 2559.99   187.5 2559.01   193.8 2559.95   207.4 2562.07   212.3 2562.17
     229  2561.5   236.1 2561.47   275.5 2562.91   293.9 2562.31   313.6 2562.85
   320.7 2563.44     324 2564.43   331.3 2568.02   334.2 2568.82   367.8 2570.32
   388.8 2572.08   391.7 2572.55   394.6 2573.62   406.1 2578.86   412.8 2579.27
#Mann= 6 ,-1,0
       0     .05       0   175.3    .045       0   193.8     .05       0
   275.5     .04       0   293.9     .03       0   412.8     .04       0
#XS Ineff= 2 , 0
          144.23 2570.35  275.21         2571.42
Permanent Ineff=
       F       F
#Block Obstruct= 1 ,-1
  354.27  412.76 2599.27
Bank Sta=175.3,193.8
XS Rating Curve= 0 ,0
Exp/Cntr(USF)=0,0
Exp/Cntr=0.3,0.1

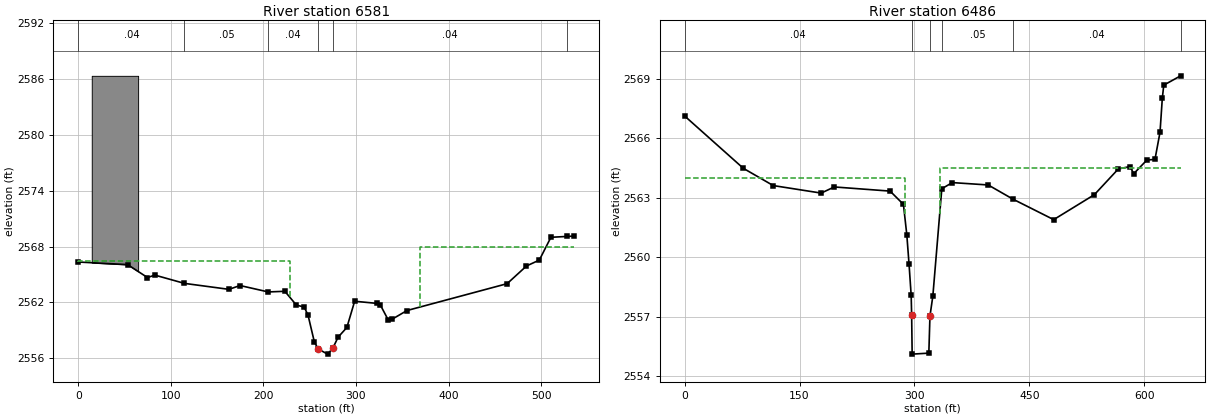
Type RM Length L Ch R = 1 ,6581    ,103.8,95.4,85.8
XS GIS Cut Line= 6
2290301.75001901467473.5001194122290246.26788665467506.799270534
 2290096.0128482467506.7150954752290008.02919243467534.118349657
2289982.77699497467662.3835087752289926.55663095467742.522846056
#Sta/Elev= 30
       0 2566.34    53.4 2566.06    74.8 2564.67    82.8 2564.93   114.8 2564.04
   162.8  2563.4   174.8 2563.81   205.3 2563.12   223.2 2563.19   235.7  2561.7
   244.1  2561.5   248.3  2560.6   255.1 2557.73259.17672556.992   269.3 2556.43
274.86872557.037   280.7 2558.25   290.2  2559.3   298.6 2562.12   322.5 2561.89
   326.5 2561.69   334.7 2560.14   338.8 2560.17   355.1 2561.12   463.3 2564.01
   484.2 2565.91   498.1 2566.55   510.6    2569   527.9 2569.09   535.7 2569.13
#Mann= 6 ,-1,0
       0     .04       0   114.8     .05       0   205.3     .04       0
259.1767    .045       0274.8687     .04       0   527.9     .03       0
#XS Ineff= 2 , 0
          228.31  2566.4  369.71         2567.92
Permanent Ineff=
       F       F
#Block Obstruct= 1 ,-1
   14.62   64.71 2586.37
Bank Sta=259.1767,274.8687
XS Rating Curve= 0 ,0
Exp/Cntr(USF)=0,0
Exp/Cntr=0.5,0.3

Type RM Length L Ch R = 1 ,6486    ,82.4,80.8,54.5
BEGIN DESCRIPTION:
XS US of structure with channel burned using survey data (SUG012CU)
END DESCRIPTION:
XS GIS Cut Line= 6
 2290171.0121022467175.9022582112290050.19558832467304.206463473
2290043.39034157 467410.185710722290007.29503162467445.517174854
2289970.77487673467653.1584371942289912.87495612467735.183324733
#Sta/Elev= 30
       0 2567.13    76.6 2564.49   115.6 2563.62   178.2 2563.24   195.3 2563.55
   268.2 2563.34   285.6 2562.67     290 2561.14   292.9 2559.67   295.7 2558.08
  296.32 2557.11     297 2555.11  318.77 2555.16320.2251 2557.03     324 2558.04
   335.7 2563.46   349.4 2563.77   396.3 2563.65   428.8 2562.93   481.8  2561.9
   534.9 2563.16   566.2 2564.46   581.4 2564.58   586.3 2564.22   603.5 2564.91
     614 2564.94   620.6 2566.31   623.6 2568.03   625.5 2568.69   647.5 2569.16
#Mann= 6 ,-1,0
       0     .04       0  296.32    .045       0320.2251     .04       0
   335.7     .05       0   428.8     .04       0   647.5     .03       0
#XS Ineff= 2 , 0
             287    2564     333          2564.5
Permanent Ineff=
       F       F
Bank Sta=296.32,320.2251
XS Rating Curve= 0 ,0
Exp/Cntr(USF)=0,0
Exp/Cntr=0.5,0.3