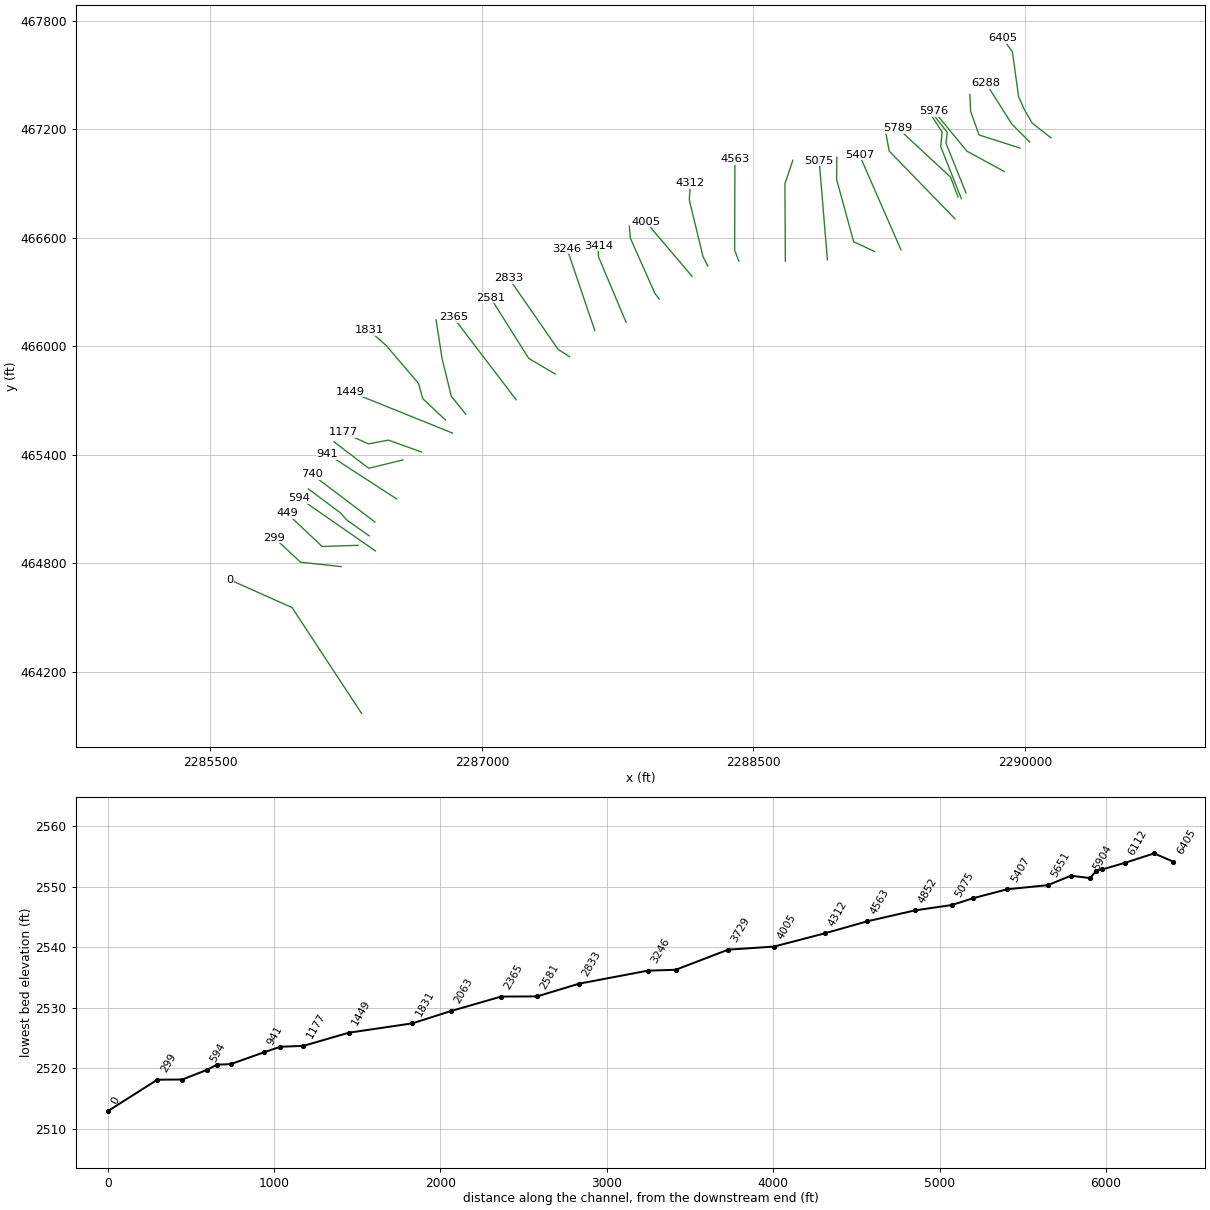
HEC-RAS study SGRCMPRN.prj: SGRCMPRN

--- SGRCMPRN.g01 (geometry) --- (continued)

Type RM Length L Ch R = 2 ,6448    ,,,
BEGIN DESCRIPTION:
Hill Country Road
Culvert 54075SUG010
8 x 10  RCP box culvert
3 ft guardrail, length of rail: approx. 75 ft (measured on imagery)
Deck width: 22 ft (measured on imagery)
Culvert length: 62 ft (measured on imagery)
Structure bounding sections incorporate channel data from survey
Deck from Lidar with survey data incorporated
END DESCRIPTION:
Bridge Culvert-0,0,0,0, 0
Deck Dist Width WeirC Skew NumUp NumDn MinLoCord MaxHiCord MaxSubmerge Is_Ogee
24,22,2.6,0, 34, 35, , , , 0, ,,,
       0    22.8    34.4    69.6    93.8   142.4   159.7   181.6   208.2   225.1
   245.8     252  276.54  276.54  298.43  331.86     351     351  359.09   360.1
   383.7     393   406.2   447.1   475.8   500.3   504.4   508.5   537.1   545.4
   550.2   574.3     580   628.3
 2565.89 2565.51  2565.4 2564.62 2564.22 2563.84  2563.8 2563.89 2563.75 2563.81
 2564.11  2563.8 2564.13 2567.13 2567.41 2567.42 2567.34 2564.34 2564.34 2564.51
 2564.33 2564.43 2564.37 2564.49 2564.83 2565.39 2565.55 2565.59 2566.55 2566.94
    2567 2567.75 2567.84 2569.14
                                                                                
                                                                                
                                                                                
                                
       0    22.8    34.4    69.6    93.8   142.4   159.7   181.6   208.2   225.1
   238.1     240     245     245  264.54  286.43  319.86  319.86  347.09   347.5
   353.1   383.7     393   406.2   447.1   475.8   500.3   504.4   508.5   537.1
   545.4   550.2   574.3     580   628.3
 2565.89 2565.51  2565.4 2564.62 2564.22 2563.84  2563.8 2563.89 2563.75 2563.81
 2563.97  2563.8  2563.8  2566.8 2567.13 2567.41 2567.42 2564.42 2564.34 2564.56
 2564.59 2564.33 2564.43 2564.37 2564.49 2564.83 2565.39 2565.55 2565.59 2566.55
 2566.94    2567 2567.75 2567.84 2569.14
                                                                                
                                                                                
                                                                                
                                        
BR Coef=-1 ,-1 , 0 ,, 0 ,,,0.8,0,,1,
WSPro=,,,, 1 ,,,, 0 ,,,, 0 ,,,,-1 ,-1 ,-1 , 0 , 0 , 0 , 0 , 0
Culvert=2,8,10,62,0.013,0.7,1,58,1,2555.106,303,2554.231,274,Culvert #1  , 0 ,11
     303     274
BC Culvert Barrel=1,barrel #1,0
Culvert Bottom n=0.013
Culvert=2,8,10,62,0.013,0.7,1,58,1,2555.163,313,2554.298,284,Culvert #2  , 0 ,11
     313     284
BC Culvert Barrel=1,barrel #2,0
Culvert Bottom n=0.013
BC Design=,, 0 ,, 0 ,,,,,,
BC Use User HTab Curves=0
BC User HTab FreeFlow(D)= 0

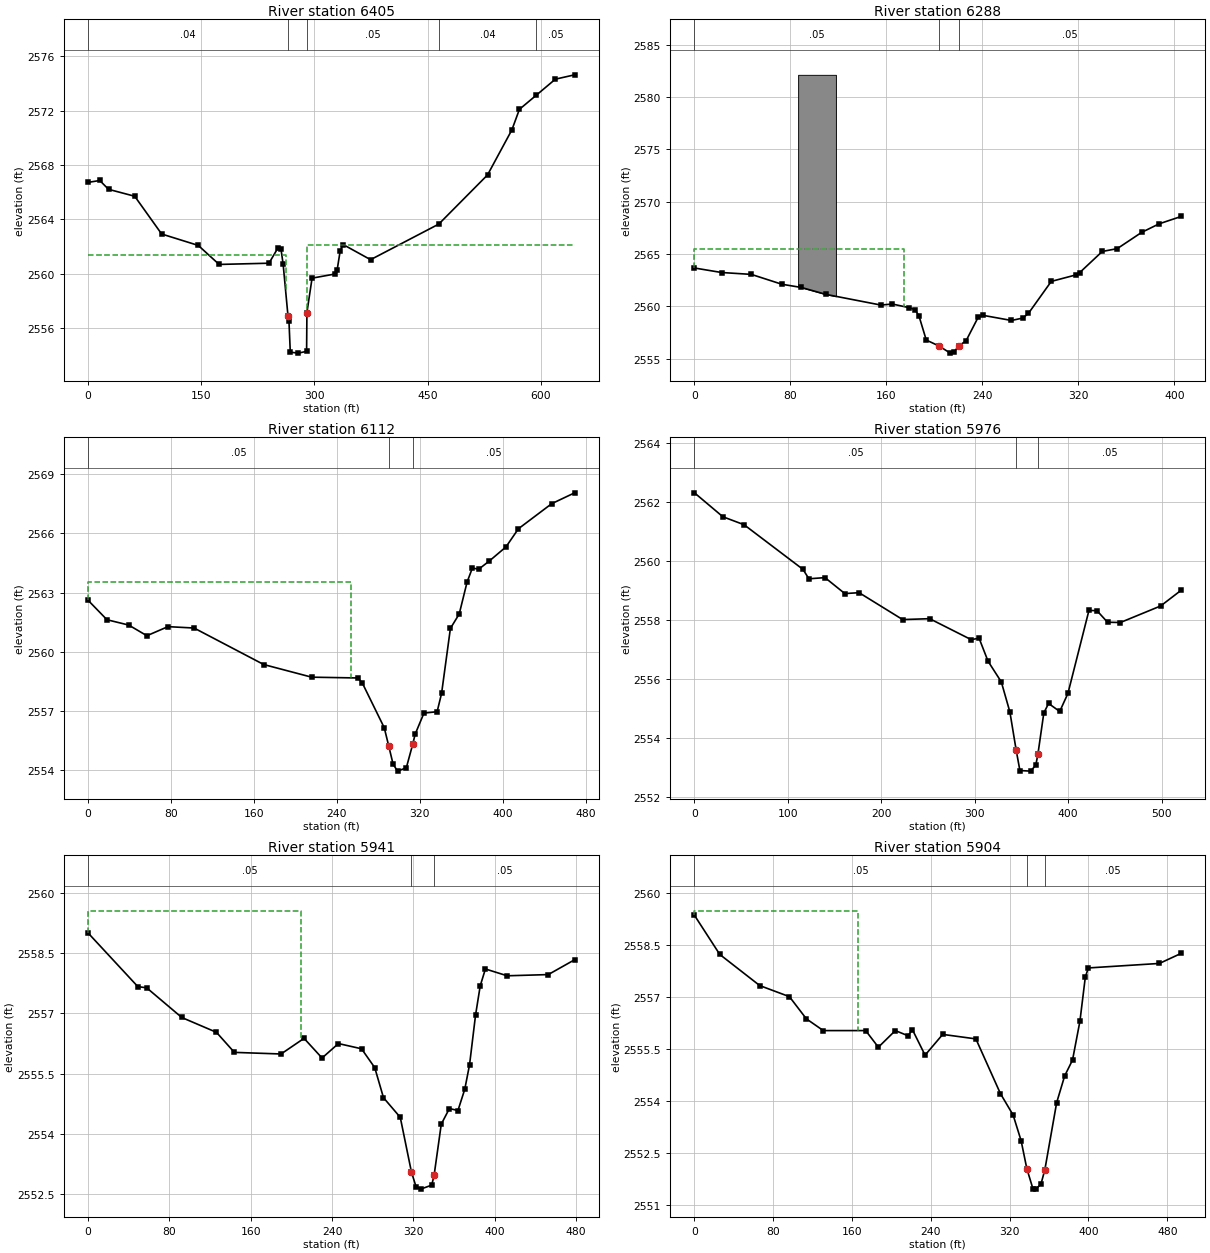
Type RM Length L Ch R = 1 ,6405    ,119.5,116.6,134
BEGIN DESCRIPTION:
XS DS of structure with channel burned using survey data (SUG008CD)
END DESCRIPTION:
XS GIS Cut Line= 6
2290144.73501859 467151.502139442290039.79957121467234.471536359
2289997.61170744467308.120461667 2289965.8105514467379.312886665
2289931.57188883467627.9793797082289876.20508974 467701.58465379
#Sta/Elev= 30
       0 2566.73    15.6 2566.87   27.22 2566.22   61.91 2565.71    97.6 2562.93
  146.11 2562.09  173.77 2560.69  239.81 2560.78  251.87 2561.92  255.79  2561.8
  258.59  2560.7 264.9652556.921  266.27 2556.55  268.05 2554.23  278.58 2554.16
  289.67 2554.29  290.08 2557.15  296.91 2559.68  326.78 2559.98  330.16 2560.29
  334.19  2561.7  338.21 2562.15  374.45 2561.04  464.82 2563.66  529.42 2567.28
   561.7  2570.6  571.67 2572.11  594.25 2573.16  619.28 2574.33  644.81 2574.65
#Mann= 5 ,-1,0
       0     .04       0 264.965    .045       0  290.08     .05       0
  464.82     .04       0  594.25     .05       0
#XS Ineff= 2 , 0
          262.06  2561.4   290.7         2562.11
Permanent Ineff=
       F       F
Bank Sta=264.965,290.08
XS Rating Curve= 0 ,0
Exp/Cntr(USF)=0,0
Exp/Cntr=0.5,0.3

Type RM Length L Ch R = 1 ,6288    ,180.3,175.9,164.1
Node Name=C
XS GIS Cut Line= 3
2290027.19451012467129.1790705312289928.15768541467228.215895241
 2289786.3857925467452.744586878
#Sta/Elev= 30
       0 2563.66    22.6 2563.23    47.4 2563.05    72.8 2562.11    89.1  2561.8
   109.6 2561.14   155.4 2560.12   164.9 2560.22     179 2559.87   183.8 2559.68
   187.1 2559.09   193.2 2556.78     2042556.202   213.2 2555.53   216.1 2555.59
   220.2 2556.23   226.3 2556.69   236.4 2558.94   240.5 2559.14   264.2 2558.65
   273.7 2558.88   278.4 2559.33   297.4 2562.38   317.6 2562.99     321 2563.21
   339.9 2565.24   352.4 2565.51   372.7 2567.06   387.3 2567.88   405.6 2568.58
#Mann= 3 ,-1,0
       0     .05       0     204    .045       0   220.2     .05       0
#XS Ineff= 2 , 0
           174.7 2565.45
Permanent Ineff=
       F       F
#Block Obstruct= 1 ,-1
    86.4   117.9 2582.11
Bank Sta=204,220.2
XS Rating Curve= 0 ,0
Exp/Cntr(USF)=0,0
Exp/Cntr=0.3,0.1

Type RM Length L Ch R = 1 ,6112    ,123.1,136.1,143.1
XS GIS Cut Line= 4
2289973.59010491467095.183299306 2289747.5446495 467167.68168156
2289700.38825334467298.8475348072289696.64528181467391.332398151
#Sta/Elev= 30
       0 2562.62    18.3 2561.63    39.3 2561.36    56.8 2560.82    77.1 2561.28
   102.3 2561.21   169.5 2559.36   215.7 2558.72   260.2 2558.68   264.5 2558.43
   285.7 2556.16     290 2555.24   294.2 2554.32   298.5 2553.96     307 2554.13
   313.1 2555.31   315.5 2555.83     324  2556.9   336.7 2556.97     341  2557.9
   349.5 2561.19     358 2561.92   365.6 2563.54   370.7 2564.25   376.8 2564.19
   386.9  2564.6   403.1 2565.32   415.1 2566.24   447.2 2567.51   469.3 2568.06
#Mann= 3 ,-1,0
       0     .05       0     290    .045       0   313.1     .05       0
#XS Ineff= 2 , 0
          253.51 2563.52
Permanent Ineff=
       F       F
Bank Sta=290,313.1
XS Rating Curve= 0 ,0
Exp/Cntr(USF)=0,0
Exp/Cntr=0.3,0.1

Type RM Length L Ch R = 1 ,5976    ,78.3,35.7,25.4
XS GIS Cut Line= 3
2289886.83712822 466965.592908812289680.08163894467078.319491796
2289498.90004031467298.690405451
#Sta/Elev= 30
       0  2562.3    30.4 2561.49    53.1 2561.22   116.1 2559.71   122.5 2559.39
   139.7 2559.43   160.9 2558.89   176.2 2558.92   222.8 2558.01   251.7 2558.04
   296.2 2557.33   304.6 2557.38   314.2  2556.6   328.4  2555.9   337.6 2554.88
   344.3 2553.59   348.3  2552.9   359.7 2552.88   365.3 2553.08   367.6 2553.46
   373.9 2554.85     379 2555.17   390.9  2554.9   399.7 2555.51   422.2 2558.32
   430.8 2558.31   442.1 2557.92   455.8 2557.91   498.9 2558.47   520.8    2559
#Mann= 3 ,-1,0
       0     .05       0   344.3    .045       0   367.6     .05       0
Bank Sta=344.3,367.6
XS Rating Curve= 0 ,0
Exp/Cntr(USF)=0,0
Exp/Cntr=0.3,0.1

Type RM Length L Ch R = 1 ,5941    ,42.4,36.9,34.5
XS GIS Cut Line= 4
2289675.02589252466847.6763334962289564.45699148467122.538502743
2289571.60083035467181.8188420312289496.23033971467278.293070059
#Sta/Elev= 30
       0 2559.01      49 2557.67    57.7 2557.64    92.2  2556.9   126.3 2556.53
   143.9 2556.03   189.8 2555.99   212.4 2556.38   230.1 2555.89   246.2 2556.25
   268.9 2556.12   281.9 2555.65   290.5  2554.9     307 2554.41317.94352553.051
   322.5 2552.68   327.1 2552.62   337.9 2552.72340.24352552.962   347.3 2554.24
   355.3 2554.63   363.7 2554.58   370.4 2555.11   375.1 2555.72     381 2556.96
   385.6 2557.69   390.7 2558.11   412.1 2557.94   452.5 2557.97   478.4 2558.34
#Mann= 3 ,-1,0
       0     .05       0317.9435    .045       0340.2435     .05       0
#XS Ineff= 2 , 0
          209.84 2559.56
Permanent Ineff=
       F       F
Bank Sta=317.9435,340.2435
XS Rating Curve= 0 ,0
Exp/Cntr(USF)=0,0
Exp/Cntr=0.3,0.1

Type RM Length L Ch R = 1 ,5904    ,58.8,115,129.5
XS GIS Cut Line= 4
2289649.62059374466815.5609674322289535.25115012 467104.34928322
2289543.49291328467184.5691112352289486.89947297467270.283448018
#Sta/Elev= 30
       0 2559.36    25.7 2558.23    66.3 2557.33    96.4 2557.01   113.6 2556.37
   130.8 2556.03   173.8 2556.03   186.7 2555.55   203.9 2556.03   216.9 2555.88
   221.2 2556.06   234.1 2555.32     252 2555.92   285.7 2555.79   310.6 2554.21
   323.5 2553.59   331.6 2552.85337.41322552.041   343.6 2551.46   346.4 2551.45
   351.7 2551.59355.71322552.013   367.7 2553.95   375.8 2554.72   383.8 2555.18
   391.3  2556.3   396.8 2557.58   399.9 2557.84     472 2557.97     494 2558.26
#Mann= 3 ,-1,0
       0     .05       0337.4132    .045       0355.7132     .05       0
#XS Ineff= 2 , 0
          166.09 2559.49
Permanent Ineff=
       F       F
Bank Sta=337.4132,355.7132
XS Rating Curve= 0 ,0
Exp/Cntr(USF)=0,0
Exp/Cntr=0.3,0.1

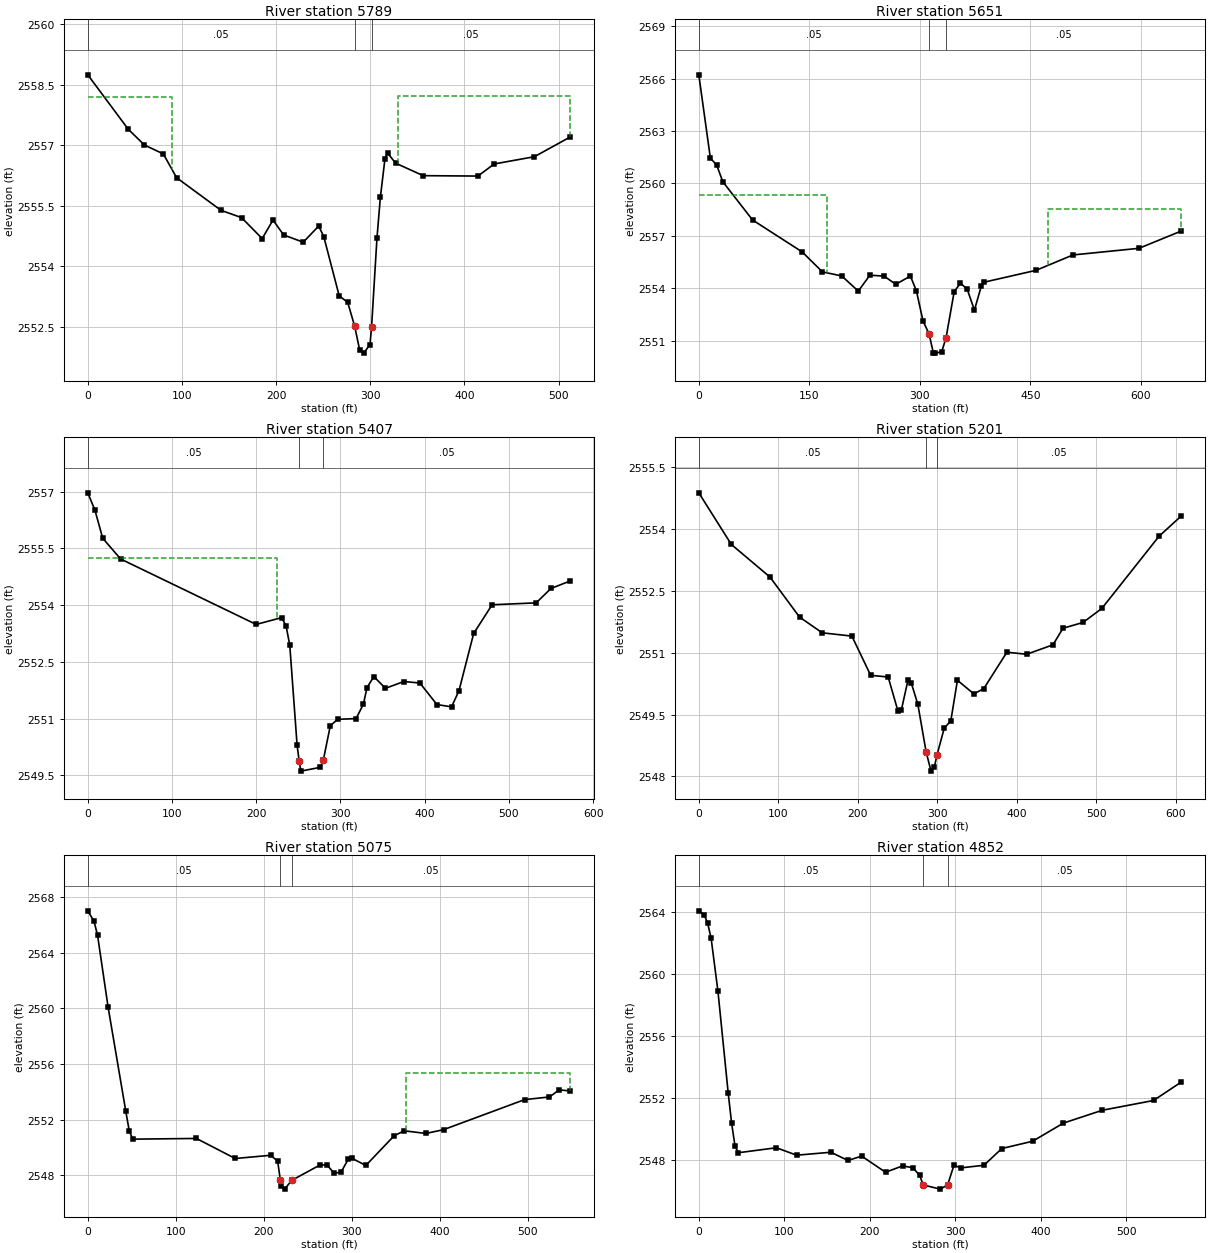
Type RM Length L Ch R = 1 ,5789    ,139.4,137.8,136.6
XS GIS Cut Line= 3
2289631.08182138466824.8688287642289590.04677647 466934.57476515
2289300.28911242 467203.39618179
#Sta/Elev= 30
       0 2558.75      43  2557.4    60.1 2557.01    80.2 2556.79    94.3  2556.2
   141.5 2555.39   163.3 2555.21   185.2 2554.69   196.7 2555.15     208 2554.78
   228.8  2554.6   245.2    2555   250.6 2554.74     267 2553.27     276 2553.11
   283.4 2552.52   288.8 2551.92     293 2551.85   299.7 2552.06   301.4 2552.51
   307.1  2554.7   310.7 2555.71   315.6 2556.67   318.4 2556.81   326.9 2556.56
   356.2 2556.25   414.3 2556.24   431.6 2556.54   474.3 2556.72   512.4 2557.21
#Mann= 3 ,-1,0
       0     .05       0   283.4    .045       0   301.4     .05       0
#XS Ineff= 2 , 0
           89.85  2558.2  329.43         2558.22
Permanent Ineff=
       F       F
Bank Sta=283.4,301.4
XS Rating Curve= 0 ,0
Exp/Cntr(USF)=0,0
Exp/Cntr=0.3,0.1

Type RM Length L Ch R = 1 ,5651    ,255,243.9,205.6
XS GIS Cut Line= 3
2289613.96952343466704.806154706 2289251.0763159467078.446301177
2289225.89993265467210.141301591
#Sta/Elev= 30
       0 2566.22    15.7 2561.45    24.2 2561.06    32.6  2560.1      73 2557.91
   140.1 2556.09   167.8 2554.94   193.9 2554.71   216.5 2553.84   232.2 2554.75
   251.4  2554.7   267.4 2554.23   287.2  2554.7   295.4 2553.85   304.2 2552.15
   312.6 2551.38   318.3 2550.31   321.2 2550.29   329.7 2550.37   335.6 2551.17
   346.6  2553.8   355.1  2554.3   364.3 2553.95   374.1 2552.75   383.4 2554.12
   387.2 2554.35   457.8 2555.03   507.9 2555.91   597.5 2556.29   654.9 2557.28
#Mann= 3 ,-1,0
       0     .05       0   312.6    .045       0   335.6     .05       0
#XS Ineff= 2 , 0
          173.49 2559.35  473.49         2558.56
Permanent Ineff=
       F       F
Bank Sta=312.6,335.6
XS Rating Curve= 0 ,0
Exp/Cntr=0.3,0.1

Type RM Length L Ch R = 1 ,5407    ,211.6,206.2,183.5
XS GIS Cut Line= 2
2289315.69647682466533.4265451542289086.22327503 467058.19857068
#Sta/Elev= 30
       0 2556.97     8.5 2556.51    17.7 2555.77      39 2555.22   199.9 2553.49
   230.3 2553.67   235.5 2553.44   239.8 2552.94   248.5 2550.29  250.89 2549.89
   252.9 2549.61   275.9 2549.71   279.7 2549.91   287.9 2550.81   296.6 2550.98
   318.5    2551   327.2 2551.38   331.5 2551.82   339.6 2552.11   353.4  2551.8
   375.2 2551.98   394.3 2551.94   414.5 2551.37   431.9 2551.31   440.7 2551.74
   458.1 2553.25     480 2554.01   532.3 2554.06   549.8 2554.44   572.8 2554.64
#Mann= 3 ,-1,0
       0     .05       0  250.89    .045       0   279.7     .05       0
#XS Ineff= 2 , 0
           224.1 2555.24
Permanent Ineff=
       F       F
Bank Sta=250.89,279.7
XS Rating Curve= 0 ,0
Exp/Cntr(USF)=0,0
Exp/Cntr=0.3,0.1

Type RM Length L Ch R = 1 ,5201    ,140.1,125.9,106.1
XS GIS Cut Line= 4
2289169.22431065466523.9800119882289054.46265823466577.742227538
2288960.37878101466922.0271848142288961.41266977467045.059947324
#Sta/Elev= 30
       0 2554.87    40.9 2553.62    89.5 2552.83   126.7 2551.86   155.2 2551.48
   192.5  2551.4   216.1 2550.45   238.1 2550.41   250.5 2549.58   254.7 2549.61
     263 2550.33   267.1 2550.27   275.4 2549.75  285.882548.591     292 2548.13
   296.2 2548.23   299.5 2548.52   308.6 2549.17   316.9 2549.35   325.2 2550.33
   345.9    2550   358.4 2550.13   387.4 2551.01   412.3 2550.96   445.4 2551.19
   457.9 2551.59   483.1 2551.73   506.8 2552.07   578.8 2553.82   606.7 2554.31
#Mann= 3 ,-1,0
       0     .05       0  285.88    .045       0   299.5     .05       0
Bank Sta=285.88,299.5
XS Rating Curve= 0 ,0
Exp/Cntr(USF)=0,0
Exp/Cntr=0.3,0.1

Type RM Length L Ch R = 1 ,5075    ,220.6,223.2,207.9
XS GIS Cut Line= 2
2288909.35639267466478.1419283632288864.00640658467024.793112016
#Sta/Elev= 30
       0    2567     7.1 2566.25    11.1 2565.24    23.1 2560.08    43.2  2552.6
    47.2 2551.17    51.2  2550.6   123.5 2550.65   167.6 2549.21   207.8 2549.44
   215.8 2549.03   218.9 2547.67   219.8 2547.24   223.8 2547.01   231.8 2547.64
   263.9 2548.74     272 2548.75     280 2548.14     288 2548.24   296.1 2549.16
   300.1 2549.23   316.1 2548.71   348.2 2550.84   359.7  2551.2   384.4 2551.01
   404.4 2551.28   496.6 2553.44   524.8 2553.63     536 2554.14   548.5 2554.06
#Mann= 3 ,-1,0
       0     .05       0   218.9    .045       0   231.8     .05       0
#XS Ineff= 2 , 0
                          362.05         2555.38
Permanent Ineff=
       F       F
Bank Sta=218.9,231.8
XS Rating Curve= 0 ,0
Exp/Cntr(USF)=0,0
Exp/Cntr=0.3,0.1

Type RM Length L Ch R = 1 ,4852    ,279.4,289,277.8
XS GIS Cut Line= 3
2288677.09326061466470.7921790822288674.79573003466898.132866792
2288718.44881103 467027.94334451
#Sta/Elev= 30
       0 2564.08     6.4 2563.82    10.4 2563.27    14.4 2562.31    22.4 2558.88
    34.4 2552.31    38.4 2550.36    42.4 2548.88    46.4 2548.47    90.8 2548.79
   114.4 2548.31   154.5  2548.5   174.4 2547.97   190.5 2548.25   218.4 2547.21
   238.4 2547.62   250.4  2547.5   258.4    2547   262.4 2546.39   282.4 2546.12
     291 2546.39   298.4 2547.66   306.4 2547.49   333.5 2547.66   354.4 2548.74
   390.4 2549.21   426.4 2550.38   471.9 2551.21   531.8 2551.84   564.3 2553.03
#Mann= 3 ,-1,0
       0     .05       0   262.4    .045       0     291     .05       0
Bank Sta=262.4,291
XS Rating Curve= 0 ,0
Exp/Cntr(USF)=0,0
Exp/Cntr=0.3,0.1

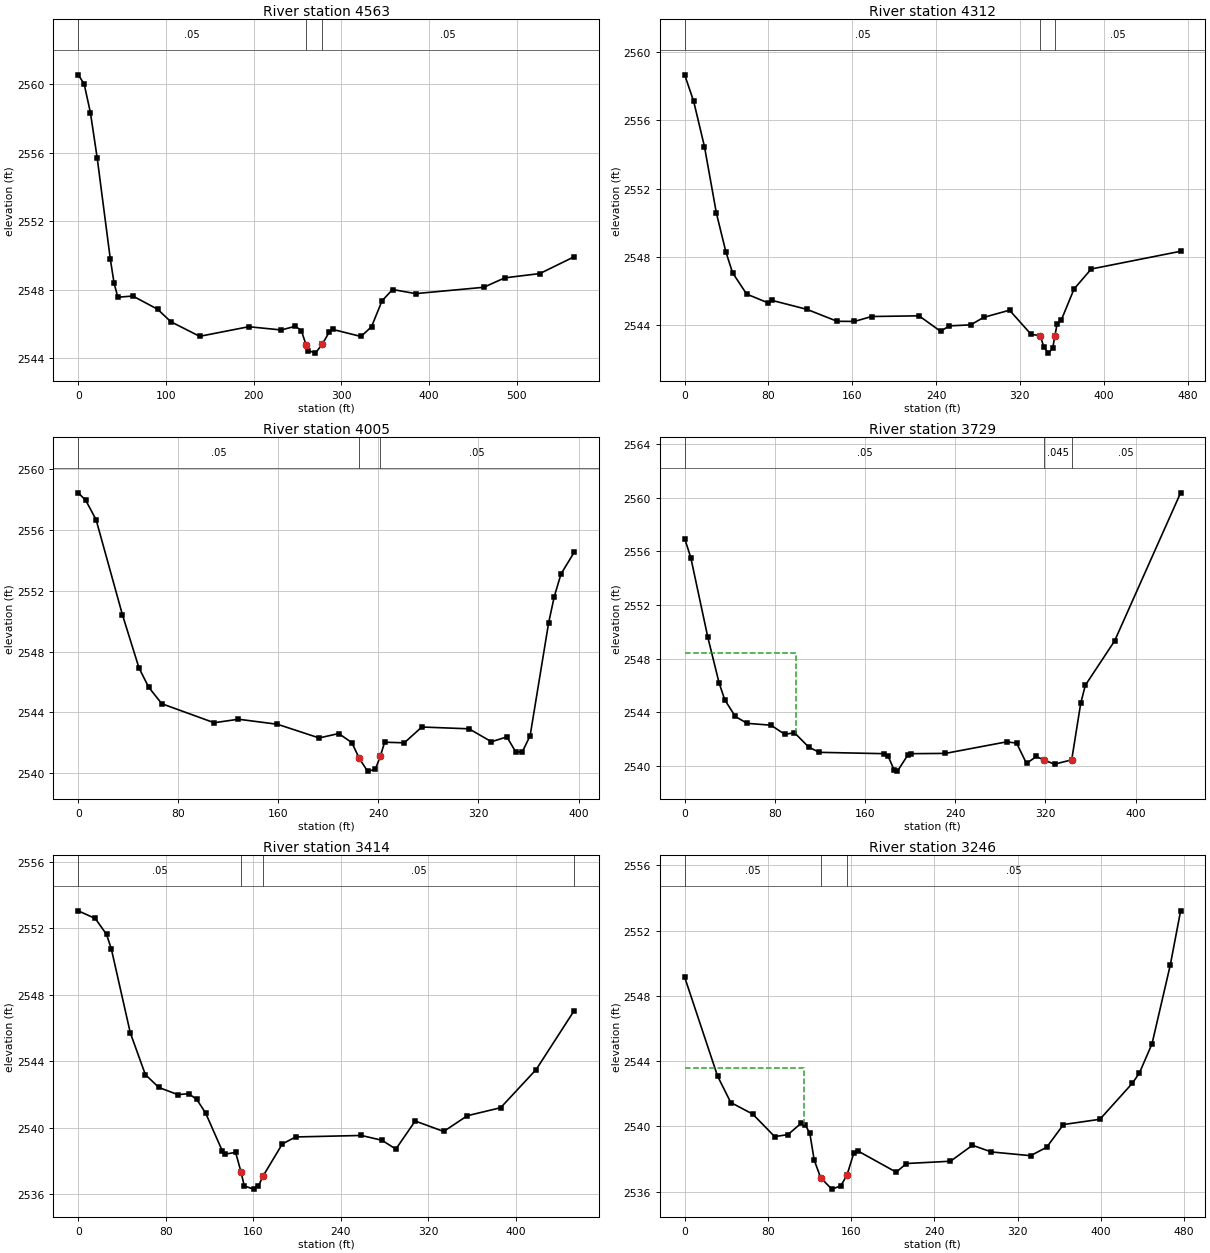
Type RM Length L Ch R = 1 ,4563    ,201.4,251,246.3
XS GIS Cut Line= 3
2288419.88967614 466470.924286772288396.79452996466531.676739428
2288398.44280084467032.261055281
#Sta/Elev= 30
       0 2560.53     6.7 2560.01    13.9 2558.33    21.7 2555.66    36.6 2549.79
    40.9 2548.38    45.2 2547.56    62.3 2547.63    90.5 2546.86   105.7 2546.13
   138.5 2545.28   194.5 2545.84   231.7 2545.65   247.7 2545.87   254.5 2545.61
   259.8 2544.79   262.5 2544.45   270.5  2544.3   278.5 2544.83   286.5 2545.55
   290.5 2545.68   322.5 2545.27   334.5 2545.84   346.5 2547.35   358.5 2548.01
   384.8 2547.77   462.5 2548.14   486.5 2548.69   526.5 2548.94   565.6 2549.92
#Mann= 3 ,-1,0
       0     .05       0   259.8    .045       0   278.5     .05       0
Bank Sta=259.8,278.5
XS Rating Curve= 0 ,0
Exp/Cntr(USF)=0,0
Exp/Cntr=0.3,0.1

Type RM Length L Ch R = 1 ,4312    ,151.7,306.9,256.7
XS GIS Cut Line= 4
2288248.05604938466444.3305713982288221.95268265466496.265819624
2288146.36369684466808.5291742072288152.52809532466902.340354646
#Sta/Elev= 30
       0 2558.68     8.6 2557.12    18.9 2554.46    30.3 2550.55    39.3 2548.29
    45.7 2547.06    59.1 2545.81    79.6 2545.29    83.8 2545.43   116.7 2544.91
   145.5 2544.21     162  2544.2   178.4 2544.49   223.7 2544.53   244.3 2543.62
   252.5 2543.94   273.1    2544   285.4 2544.44   310.1 2544.86   330.7 2543.44
   339.3 2543.37     343 2542.68   347.2 2542.34   351.3 2542.63  353.322543.327
   355.4 2544.03   359.5 2544.28   371.7 2546.11   388.1 2547.28   473.4 2548.32
#Mann= 3 ,-1,0
       0     .05       0   339.3    .045       0  353.32     .05       0
Bank Sta=339.3,353.32
XS Rating Curve= 0 ,0
Exp/Cntr(USF)=0,0
Exp/Cntr=0.3,0.1

Type RM Length L Ch R = 1 ,4005    ,191,276,133.3
XS GIS Cut Line= 2
2288161.72027218466386.238217202 2287905.4271758466688.751563216
#Sta/Elev= 30
       0 2558.43       6 2557.94    14.3 2556.66    35.3 2550.43    48.6 2546.92
    56.3 2545.66    66.8 2544.57   108.7 2543.32   128.1 2543.55   159.3 2543.22
   192.6 2542.32   208.3 2542.61   218.8 2542.01   224.6 2540.99   231.3 2540.14
   237.5 2540.25   241.6 2541.14     245 2542.04   260.7    2542   274.7 2543.04
   312.5 2542.92   330.4 2542.07   342.7 2542.39   349.9 2541.39   355.1 2541.41
   361.3 2542.47   376.1 2549.89   380.6 2551.61     386  2553.1   396.5 2554.52
#Mann= 3 ,-1,0
       0     .05       0   224.6    .045       0   241.6     .05       0
Bank Sta=224.6,241.6
XS Rating Curve= 0 ,0
Exp/Cntr(USF)=0,0
Exp/Cntr=0.3,0.1

Type RM Length L Ch R = 1 ,3729    ,210.1,314.5,211.9
XS GIS Cut Line= 4
2287980.22657495466260.8394541982287955.76307707 466293.20811925
2287820.49081776466597.6147348762287815.02426053466663.570883623
#Sta/Elev= 30
       0 2556.95     5.4 2555.54    20.5 2549.61    30.5 2546.21    35.5 2544.95
    44.9  2543.7    55.4 2543.19    76.6 2543.05    88.8 2542.37    97.4 2542.49
   109.9 2541.43   119.3 2541.03   176.6 2540.93   180.6 2540.72   185.7 2539.73
   188.7 2539.63   197.8 2540.81   200.9 2540.93   231.2 2540.95   285.5 2541.81
   294.4 2541.72   303.2  2540.2   311.9 2540.72     319 2540.44   328.1 2540.15
   343.3 2540.47   351.3 2544.69   355.4 2546.03   381.3 2549.32   439.9 2560.36
#Mann= 3 ,-1,0
       0     .05       0     319    .045       0   343.3     .05       0
#XS Ineff= 2 , 0
            98.9 2548.43
Permanent Ineff=
       F       F
Bank Sta=319,343.3
XS Rating Curve= 0 ,0
Exp/Cntr(USF)=0,0
Exp/Cntr=0.3,0.1

Type RM Length L Ch R = 1 ,3414    ,169.7,168.4,156.7
XS GIS Cut Line= 3
2287796.69872932466133.2755859862287644.04410137466495.622477252
2287643.25322093466555.801778014
#Sta/Elev= 30
       0 2553.06    15.6  2552.6    25.9 2551.64    30.3 2550.76    47.6 2545.72
    61.4  2543.2    73.7 2542.43      91    2542   101.1 2542.05   108.4 2541.71
   116.4  2540.9   131.6 2538.63   134.5 2538.42   143.9 2538.52   148.8 2537.35
   151.8  2536.5   160.5 2536.31   164.8 2536.51   169.2 2537.12   186.6 2539.03
   198.8 2539.45   258.9 2539.54   277.7 2539.25   290.4 2538.72   308.1 2540.41
   334.1 2539.78   355.8 2540.73   386.2 2541.21   418.7 2543.51   453.4 2547.05
#Mann= 4 ,-1,0
       0     .05       0   148.8    .045       0   169.2     .05       0
  453.19      .1       0
Bank Sta=148.8,169.2
XS Rating Curve= 0 ,0
Exp/Cntr(USF)=0,0
Exp/Cntr=0.3,0.1

Type RM Length L Ch R = 1 ,3246    ,267,412.7,330.5
Node Name=B
XS GIS Cut Line= 2
2287624.06622326466087.2626047052287470.81289227 466538.64809869
#Sta/Elev= 30
       0 2549.15    31.6 2543.09    44.3 2541.47    65.4 2540.76    86.5 2539.38
    99.2  2539.5   111.8 2540.19   116.1 2540.08   120.3 2539.58   124.5 2537.94
   130.7 2536.86   141.4 2536.16   149.9 2536.35   155.9    2537   162.5 2538.36
   166.8 2538.49   203.3  2537.2   213.2 2537.73   255.5 2537.87   276.6 2538.85
   294.7 2538.44   332.5 2538.21     348 2538.73   364.1 2540.12   399.1 2540.44
   430.3 2542.65   437.1 2543.28   449.2 2545.07   466.7 2549.88   476.7 2553.22
#Mann= 3 ,-1,0
       0     .05       0   130.7    .045       0   155.9     .05       0
#XS Ineff= 2 , 0
          114.96 2543.56
Permanent Ineff=
       F       F
Bank Sta=130.7,155.9
XS Rating Curve= 0 ,0
Exp/Cntr(USF)=0,0
Exp/Cntr=0.3,0.1

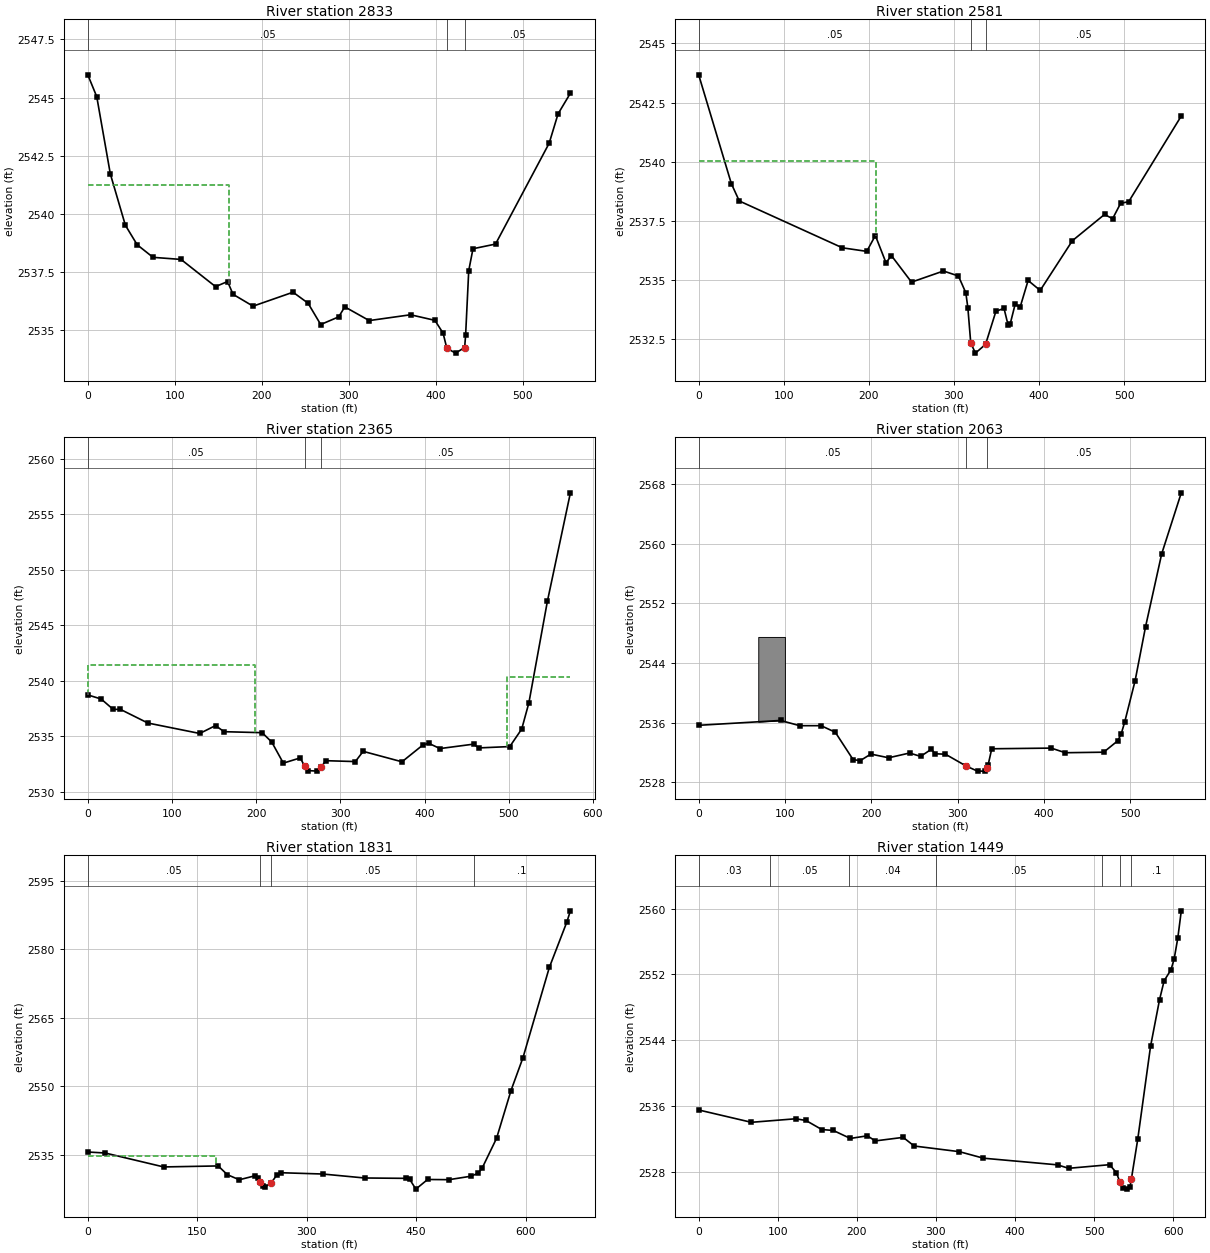
Type RM Length L Ch R = 1 ,2833    ,157.8,252.4,177.7
XS GIS Cut Line= 3
2287484.80420329465941.9400061022287420.56589851465984.256267487
2287148.53648404466377.298733841
#Sta/Elev= 30
       0 2545.98    10.3 2545.04    25.9 2541.72    43.2 2539.51    56.8 2538.67
      75 2538.13   107.2 2538.04   146.9 2536.87   160.7 2537.09     167 2536.54
     190 2536.03     236 2536.63   253.2 2536.16   267.8 2535.24   288.5 2535.57
   295.5    2536   323.6 2535.41   371.1 2535.66   399.1 2535.42   408.5 2534.87
  412.822534.219   422.9 2534.01433.28922534.252   434.4 2534.77     438 2537.56
   442.9  2538.5   468.8  2538.7   530.5 2543.04   540.7  2544.3   554.9 2545.19
#Mann= 3 ,-1,0
       0     .05       0  412.82    .045       0433.2892     .05       0
#XS Ineff= 2 , 0
          162.05 2541.23
Permanent Ineff=
       F       F
Bank Sta=412.82,433.2892
XS Rating Curve= 0 ,0
Exp/Cntr(USF)=0,0
Exp/Cntr=0.3,0.1

Type RM Length L Ch R = 1 ,2581    ,202.9,216.2,215.6
XS GIS Cut Line= 3
2287405.23507612465847.0100307612287258.88944534465933.297571858
2287047.33788862466269.500306558
#Sta/Elev= 30
       0 2543.67    38.4 2539.07    47.7 2538.34   168.9 2536.36   197.5 2536.21
   207.6 2536.88   220.1 2535.73   226.5 2536.03   250.1 2534.91   287.6 2535.38
   305.2 2535.17   313.9 2534.46   316.3 2533.83   319.7 2532.34   325.2 2531.91
   337.1 2532.28   349.3 2533.68   358.8  2533.8   363.5 2533.11   366.1 2533.15
   371.9 2533.98   377.7 2533.85   387.1 2534.98   401.3 2534.56   439.1 2536.66
   476.9 2537.77   486.4 2537.59   495.8 2538.24   505.3 2538.31   567.1 2541.93
#Mann= 3 ,-1,0
       0     .05       0   319.7    .045       0   337.1     .05       0
#XS Ineff= 2 , 0
          207.83 2540.04
Permanent Ineff=
       F       F
Bank Sta=319.7,337.1
XS Rating Curve= 0 ,0
Exp/Cntr(USF)=0,0
Exp/Cntr=0.3,0.1

Type RM Length L Ch R = 1 ,2365    ,253.4,301.4,183.7
XS GIS Cut Line= 2
2287189.76482941465704.5144233812286842.28588195466160.208243047
#Sta/Elev= 30
       0 2538.74    15.9 2538.37    30.1 2537.44    38.7 2537.44    71.3 2536.21
   132.9 2535.27   151.7 2535.98   161.8 2535.43   207.1 2535.34   218.5 2534.49
   232.2  2532.6   252.3 2533.07   257.4 2532.34   261.3 2531.93   272.5 2531.88
   277.5 2532.26   282.5 2532.82   317.7 2532.74     327 2533.66   373.1 2532.72
   398.2 2534.25     405 2534.38   418.2 2533.91   458.2 2534.31   464.4 2533.97
   501.1 2534.09   515.3 2535.67   523.8 2538.03   545.8 2547.18   573.1 2556.93
#Mann= 3 ,-1,0
       0     .05       0   257.4    .045       0   277.5     .05       0
#XS Ineff= 2 , 0
           198.8  2541.4  497.76         2540.32
Permanent Ineff=
       F       F
Bank Sta=257.4,277.5
XS Rating Curve= 0 ,0
Exp/Cntr(USF)=0,0
Exp/Cntr=0.3,0.1

Type RM Length L Ch R = 1 ,2063    ,157.7,231.8,231.9
XS GIS Cut Line= 4
2286911.50671969465624.0827253122286831.27044346465724.008634871
 2286779.9589512465933.5469267612286747.20297452466146.005396803
#Sta/Elev= 30
       0 2535.64    94.8 2536.29     117 2535.59   141.7 2535.59   158.2 2534.71
   178.8 2531.04     187 2530.89   199.4 2531.78     220 2531.28   244.2 2531.92
     257 2531.47   269.4 2532.42   273.9 2531.82   285.8 2531.76 309.7752530.172
   322.9 2529.49   331.1 2529.49333.38822529.974   335.3 2530.37   339.4 2532.49
   408.3 2532.58   424.5 2531.96     469 2532.03   485.2 2533.55   489.2 2534.44
   493.3 2536.05   505.4 2541.61   517.5 2548.86   536.2 2558.65   558.9 2566.84
#Mann= 3 ,-1,0
       0     .05       0 309.775    .045       0333.3882     .05       0
#Block Obstruct= 1 ,-1
      69   99.85  2547.5
Bank Sta=309.775,333.3882
XS Rating Curve= 0 ,0
Exp/Cntr(USF)=0,0
Exp/Cntr=0.3,0.1

Type RM Length L Ch R = 1 ,1831    ,176.6,382.2,296.8
XS GIS Cut Line= 5
2286798.85659432465592.8686912512286673.74157985465710.446656661
2286650.00217862465794.8188183582286472.54304998466003.092158044
 2286376.4859051466088.353227959
#Sta/Elev= 30
       0 2535.59    23.8 2535.37     104 2532.32   178.7 2532.54   191.2 2530.63
   207.6 2529.51   228.6 2530.36   232.7 2529.98235.83872529.041     240 2528.13
   243.3 2527.97   251.3 2528.81   259.3 2530.61   265.1 2531.05   321.9 2530.77
   379.3  2529.9   435.9 2529.82   441.1 2529.62   449.6 2527.46   465.7 2529.57
     495 2529.53   525.2 2530.29   534.7 2530.93   540.4 2532.05   560.2 2538.59
     580 2549.06   596.4 2556.25   632.5    2576   656.5 2585.95   661.4 2588.41
#Mann= 4 ,-1,0
       0     .05       0235.8387    .045       0   251.3     .05       0
  529.34      .1       0
#XS Ineff= 2 , 0
           175.3  2534.7
Permanent Ineff=
       F       F
#Block Obstruct= 2 , 0
           18.44 2555.59
Bank Sta=235.8387,251.3
XS Rating Curve= 0 ,0
Exp/Cntr(USF)=0,0
Exp/Cntr=0.3,0.1

Type RM Length L Ch R = 1 ,1449    ,197.2,272.8,258
XS GIS Cut Line= 2
2286837.99911653465520.3646539762286272.07002755465748.854740705
#Sta/Elev= 30
       0 2535.53    66.6 2534.03   122.8 2534.46   135.7 2534.25   155.7 2533.15
   170.2 2533.04   191.8 2532.07   213.3 2532.39   223.3 2531.77   258.6  2532.2
   272.5 2531.15   329.8 2530.46     360 2529.67   453.8 2528.86   467.8 2528.44
   519.6 2528.88   528.2 2527.92   532.6 2526.79   536.9 2526.06   541.2 2525.91
   545.5 2526.21   547.1 2527.09   555.2 2531.95   571.4 2543.25   582.8 2548.93
   588.6 2551.23   597.3 2552.57   601.3 2553.89   605.9 2556.43   610.3 2559.73
#Mann= 7 ,-1,0
       0     .03       0      90     .05       0     190     .04       0
     300     .05       0     510      .1       0   532.6    .045       0
   547.1      .1       0
Bank Sta=532.6,547.1
XS Rating Curve= 0 ,0
Exp/Cntr(USF)=0,0
Exp/Cntr=0.3,0.1

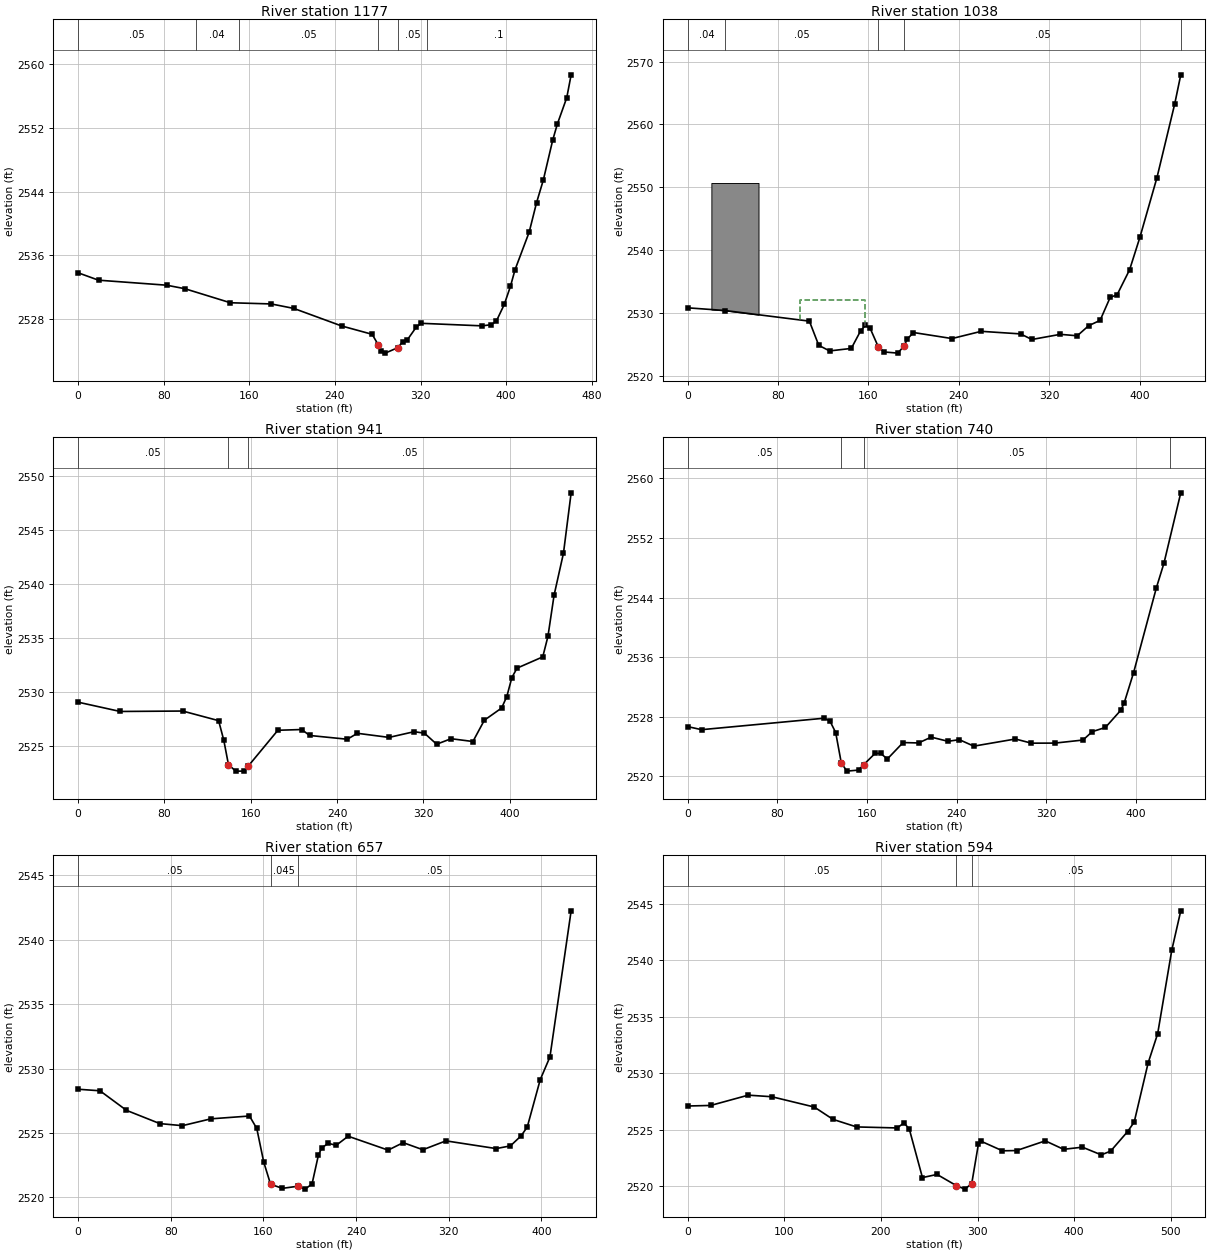
Type RM Length L Ch R = 1 ,1177    ,144.8,138.1,108.7
XS GIS Cut Line= 4
2286666.14271024465416.1593171692286483.26747333465481.595152947
2286373.38818002465460.6007015082286232.41100706465524.139709043
#Sta/Elev= 30
       0 2533.82    19.1 2532.89    82.8 2532.26    99.8 2531.82   142.3 2530.06
   180.5 2529.91   201.5 2529.35   246.2 2527.15   274.8  2526.1280.52112524.768
   282.9 2524.02     287 2523.74299.07572524.445   303.2 2525.18   307.5 2525.38
   316.2 2527.04   320.6 2527.48   377.6 2527.16   386.1 2527.31   390.8 2527.75
   398.2 2529.84     404 2532.12   408.3 2534.21   421.5 2538.92   428.4 2542.62
   434.7 2545.45   443.5 2550.47   447.8 2552.47   456.6 2555.78   460.7 2558.65
#Mann= 6 ,-1,0
       0     .05       0     110     .04       0     150     .05       0
280.5211    .045       0299.0757     .05       0   326.1      .1       0
Bank Sta=280.5211,299.0757
XS Rating Curve= 0 ,0
Exp/Cntr(USF)=0,0
Exp/Cntr=0.3,0.1

Type RM Length L Ch R = 1 ,1038    ,105.8,97.5,64.2
XS GIS Cut Line= 3
2286564.82627344465372.376957226  2286375.004297465325.851962999
2286183.32132078465471.940444872
#Sta/Elev= 30
       0  2530.8      33 2530.37   107.7 2528.68     116 2524.83   125.6 2523.94
   144.8 2524.34   153.1 2527.15   157.2    2528   161.3 2527.61   168.6 2524.63
   173.6 2523.78     186 2523.59   191.7 2524.78   194.2 2525.79   199.8 2526.87
   233.9 2525.91   259.8 2527.06   294.6 2526.65   304.6 2525.76   329.8 2526.58
   344.8 2526.35   354.9 2527.96     365  2528.8   373.9 2532.45   380.1 2532.89
   391.1 2536.85   400.2    2542   415.3  2551.5     431 2563.21   436.4 2567.88
#Mann= 5 ,-1,0
       0     .04       0      33     .05       0   168.6    .045       0
   191.7     .05       0   436.4      .1       0
#XS Ineff= 1 ,-1
      99     157    2532
Permanent Ineff=
       T
#Block Obstruct= 1 ,-1
   20.96   62.68 2550.67
Bank Sta=168.6,191.7
XS Rating Curve= 0 ,0
Exp/Cntr(USF)=0,0
Exp/Cntr=0.3,0.1

Type RM Length L Ch R = 1 ,941     ,170.7,201.3,155.7
XS GIS Cut Line= 2
2286529.46727783465156.500984014 2286146.1013254465404.944453185
#Sta/Elev= 30
       0 2529.07      39 2528.21    96.9 2528.25   130.2 2527.36     135 2525.55
   139.32523.302     146 2522.69   154.1 2522.69   157.6 2523.15   185.1 2526.47
   207.2 2526.54   214.5 2525.99   249.4 2525.64   258.8 2526.19   288.1 2525.81
   311.4 2526.34   320.9  2526.2   332.2 2525.18   345.6 2525.69   365.8 2525.43
   376.4  2527.4   392.4 2528.53   397.2 2529.59   401.9 2531.35   406.7 2532.22
   430.5 2533.26   435.3 2535.15     441 2538.97   449.7 2542.86   456.8 2548.44
#Mann= 3 ,-1,0
       0     .05       0   139.3    .045       0   157.6     .05       0
Bank Sta=139.3,157.6
XS Rating Curve= 0 ,0
Exp/Cntr(USF)=0,0
Exp/Cntr=0.3,0.1

Type RM Length L Ch R = 1 ,740     ,85.1,82.7,76.1
XS GIS Cut Line= 2
2286409.43279273465029.0224998332286058.63433626465294.214966925
#Sta/Elev= 30
       0 2526.69    12.4 2526.28   121.9 2527.82   126.9 2527.43     132  2525.9
     137 2521.82     142 2520.72   152.4 2520.86     157 2521.59   167.1 2523.09
   172.1  2523.1   178.1 2522.35   192.1 2524.55   205.9  2524.5   217.2 2525.28
   232.2 2524.72   242.3 2524.94   255.2 2524.07   292.3 2525.03   306.6 2524.47
   327.5 2524.48   352.6 2524.89   360.8 2526.01   372.6 2526.58   386.5 2528.92
   389.4  2529.9   397.7 2533.92   418.1 2545.34   424.8 2548.61   439.8 2558.05
#Mann= 4 ,-1,0
       0     .05       0     137    .045       0     157     .05       0
     430      .1       0
Bank Sta=137,157
XS Rating Curve= 0 ,0
Exp/Cntr(USF)=0,0
Exp/Cntr=0.3,0.1

Type RM Length L Ch R = 1 ,657     ,63.8,62.5,65.9
Node Name=A
XS GIS Cut Line= 4
2286377.79579665464952.5088621622286254.16934937465039.871551576
2286216.25723887465081.6298182152286041.53186004465211.849676021
#Sta/Elev= 30
       0 2528.39    18.9 2528.27    41.8 2526.75    70.6 2525.72    90.1 2525.56
   114.6 2526.09     148 2526.31   154.3 2525.34   160.3 2522.73   166.2 2521.01
   176.4 2520.69   190.1 2520.86     196 2520.63     202 2521.03   207.5 2523.27
   210.4 2523.84   216.1 2524.19   222.8 2524.03   233.2 2524.74   267.7 2523.66
   280.7 2524.24   297.7 2523.69   317.6 2524.38     361 2523.78   373.3 2523.99
   382.5 2524.77   387.8 2525.45     399 2529.13   407.4  2530.9   425.7 2542.25
#Mann= 3 ,-1,0
       0     .05       0   166.2    .045       0   190.1     .05       0
Bank Sta=166.2,190.1
XS Rating Curve= 0 ,0
Exp/Cntr(USF)=0,0
Exp/Cntr=0.3,0.1

Type RM Length L Ch R = 1 ,594     ,147.6,145.1,134.4
XS GIS Cut Line= 2
2286411.72059497464869.4302672462285992.53964248465160.650718449
#Sta/Elev= 30
       0  2527.1    23.8 2527.15    62.7 2528.06    87.1 2527.92     131 2527.01
   150.4 2525.92   174.8 2525.25   216.9 2525.16   223.9 2525.61   229.4 2525.06
     243 2520.77   258.1 2521.05  278.022520.065   286.8 2519.75     294 2520.23
     301 2523.77   304.1 2523.97   325.8 2523.14   340.4 2523.16   370.2 2524.02
   389.1 2523.27   408.6 2523.46   428.1 2522.78   437.8 2523.11   455.3 2524.83
   462.2 2525.68   476.6  2530.9   486.5  2533.5   501.1 2540.88   510.4 2544.36
#Mann= 3 ,-1,0
       0     .05       0  278.02    .045       0     294     .05       0
Bank Sta=278.02,294
XS Rating Curve= 0 ,0
Exp/Cntr(USF)=0,0
Exp/Cntr=0.3,0.1

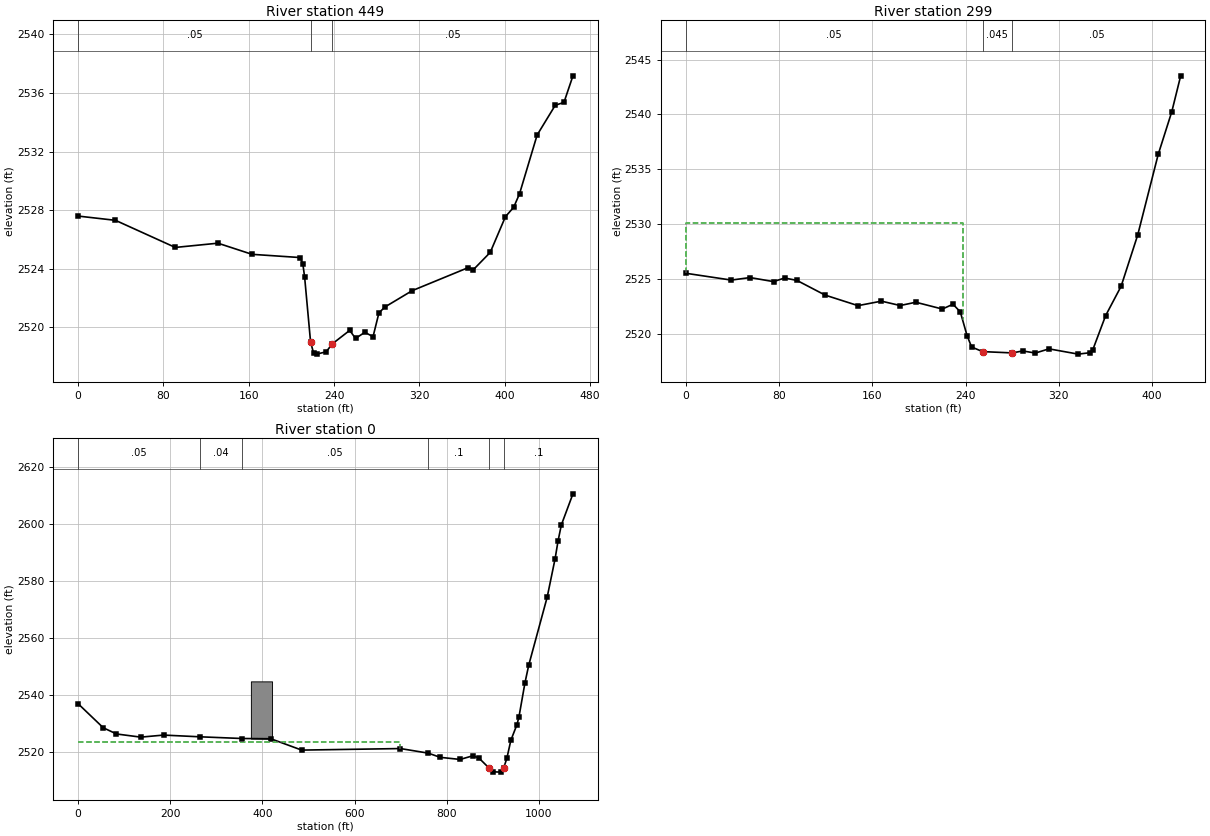
Type RM Length L Ch R = 1 ,449     ,149.3,150.5,147.2
XS GIS Cut Line= 3
2286315.15839669464900.3110288642286117.90553192464893.717618342
2285923.67532157465076.533516872
#Sta/Elev= 30
       0  2527.6      35 2527.31    91.1 2525.46   131.1 2525.75   163.1 2524.99
   208.2 2524.77   210.7 2524.36   212.4 2523.46     218 2519.01   220.8 2518.26
   223.7 2518.18   232.7 2518.34   238.2 2518.87   254.7  2519.8   260.2 2519.25
   268.9 2519.67   276.6 2519.37   282.1 2520.99   287.6 2521.39   313.3 2522.51
   365.8 2524.08   370.8 2523.95   386.5 2525.12   400.8 2527.56   408.5  2528.2
     414 2529.12   430.5 2533.13   447.5 2535.16   455.7 2535.36   464.1 2537.17
#Mann= 3 ,-1,0
       0     .05       0     218    .045       0   238.2     .05       0
Bank Sta=218,238.2
XS Rating Curve= 0 ,0
Exp/Cntr(USF)=0,0
Exp/Cntr=0.3,0.1

Type RM Length L Ch R = 1 ,299     ,289.7,298.8,309.2
XS GIS Cut Line= 3
2286222.97373282464782.6808864082285997.89318588464806.958971024
2285853.13861332464942.338025399
#Sta/Elev= 30
       0 2525.52      39  2524.9    55.1 2525.13    75.2 2524.76    84.7 2525.09
    95.3 2524.87   119.5 2523.53   147.7 2522.57   167.8 2522.98   183.9 2522.58
   197.3 2522.88   220.1 2522.26   229.2  2522.7   235.5    2522   241.3 2519.83
   245.2  2518.8   254.6 2518.38   280.1 2518.26     289 2518.44   299.9 2518.25
   311.6 2518.63   336.7 2518.15   346.8 2518.28   349.2 2518.55   360.2 2521.66
   373.5 2524.34   387.7    2529   405.3 2536.35     417 2540.26   424.6 2543.52
#Mann= 3 ,0,0
       0     .05       0   254.6    .045       0   280.1     .05       0
#XS Ineff= 2 , 0
          237.45 2530.14
Permanent Ineff=
       F       F
Bank Sta=254.6,280.1
XS Rating Curve= 0 ,0
Exp/Cntr(USF)=0,0
Exp/Cntr=0.3,0.1

Type RM Length L Ch R = 1 ,0       ,529.1,507,504
XS GIS Cut Line= 3
2286335.40810812463971.6434162612285951.14141113464556.356051054
2285609.07254052464708.971393325
#Sta/Elev= 30
       0 2536.93    54.5 2528.51    83.2 2526.33   135.9 2525.22   185.4 2525.94
   265.1 2525.33   355.5 2524.74   418.3 2524.65   485.3 2520.67   699.7 2521.21
   759.9 2519.61   786.1 2518.13   829.3 2517.39   856.2 2518.65   869.4 2517.99
   892.7 2514.28     900 2513.06   917.5 2512.94   923.92514.436   930.7 2517.77
   939.4  2524.1   952.6  2529.6     957 2532.32   970.1 2544.34   978.2 2550.46
  1018.3 2574.36  1035.5 2587.86  1041.8    2594    1049 2599.67  1074.2  2610.6
#Mann= 6 ,-1,0
       0     .05       0   265.1     .04       0   355.5     .05       0
   759.9      .1       0   892.7    .045       0   923.9      .1       0
#XS Ineff= 2 , 0
          698.21 2523.46
Permanent Ineff=
       F       F
#Block Obstruct= 1 ,-1
     375  420.96 2544.79
Bank Sta=892.7,923.9
XS Rating Curve= 0 ,0
Exp/Cntr(USF)=0,0
Exp/Cntr=0.3,0.1
LCMann Table=0

Chan Stop Cuts=-1
Use User Specified Reach Order=0
Composite Channel Slope=5